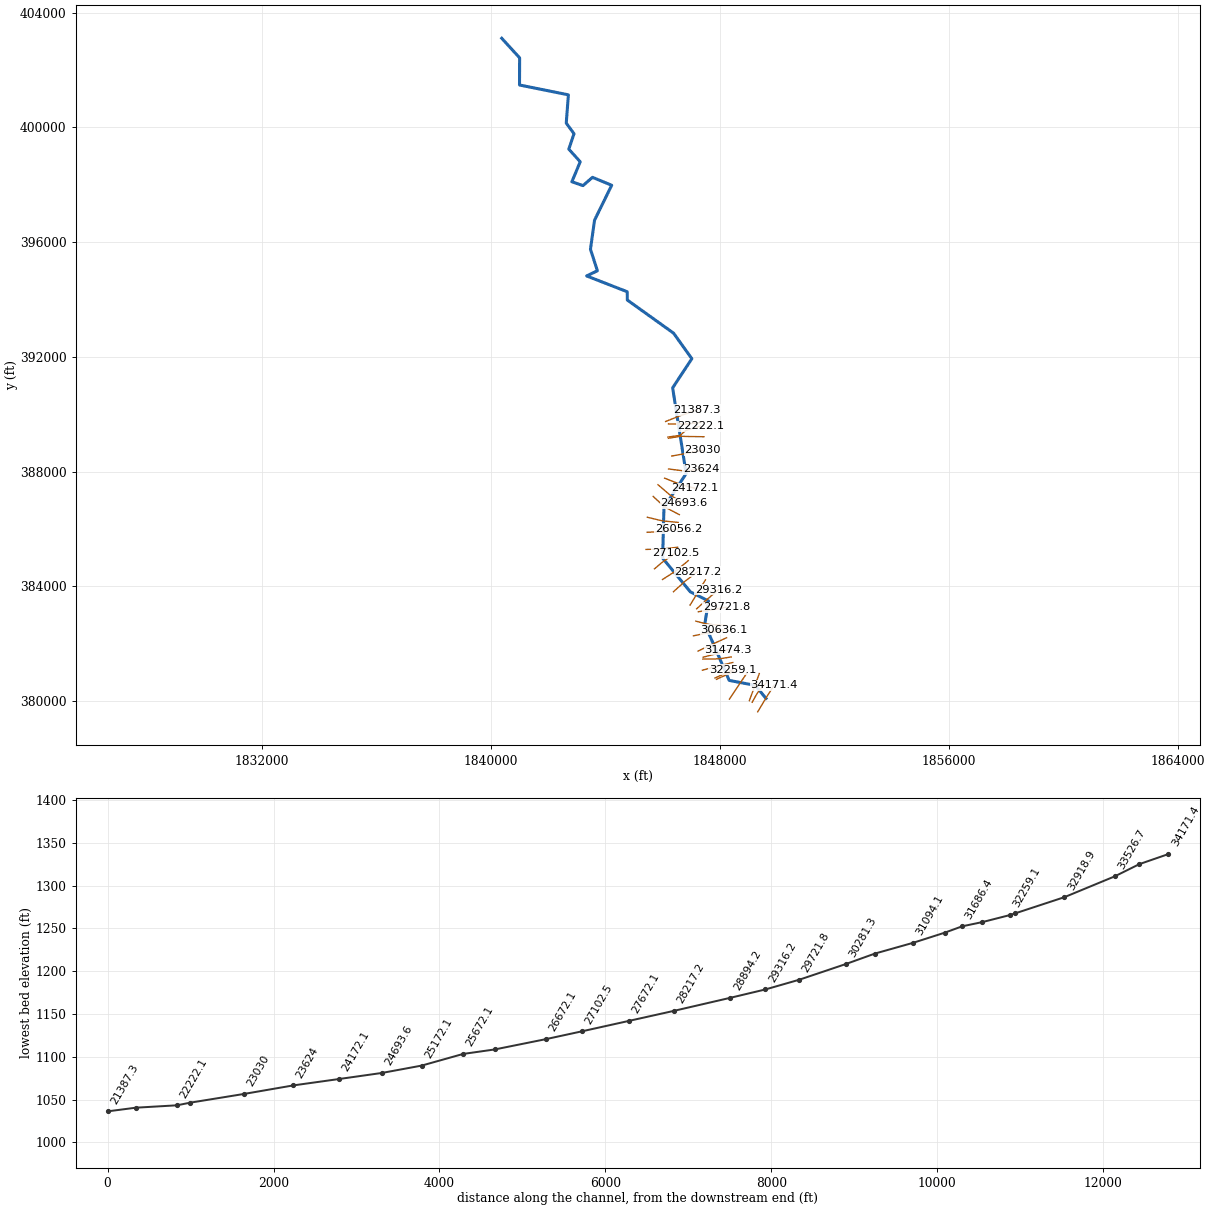
--- CobunCk.prj (project) ---

Proj Title=CobunCk
Current Plan=p01
Default Exp/Contr=0,0
English Units
Geom File=g01
Flow File=f01
Plan File=p01
BEGIN DESCRIPTION:
END DESCRIPTION:
DSS Export Rating Curves= 0
DSS Export Rating Curve Sorted= 0
DSS Export Volume Flow Curves= 0
DXF OffsetX= 0
DXF OffsetY= 0
DXF ScaleX= 0
DXF ScaleY= 0

--- CobunCk.p01 (plan) ---

Plan Title=Floodplain
Program Version=4.00
Geom File=g01
Flow File=f01
K Sum by GR=0
Std Step Tol=0.01
Critical Tol=0.01
Num of Std Step Trials=20
Max Error Tol=0.3
Flow Tol Ratio=0.001
Split Flow NTrial=30
Split Flow Tol=0.02
Split Flow Ratio=0.02
Log Output Level=0
Friction Slope Method=1
Unsteady Friction Slope Method=2
Unsteady Bridges Friction Slope Method=1
Global Log Level=0
CheckData=False
Run HTab=0
Run UNet=0
Run PostProcess=0
UNET Theta=0
UNET Theta Warmup=0
UNET ZTol=0
UNET ZSATol=0
UNET MxIter=0
UNET MaxInSteps=0
UNET DtIC=0
UNET DtMin=0
UNET MaxCRTS=0
UNET WFStab=0
UNET SFStab=0
UNET WFX=0
UNET SFX=0
UNET DSS MLevel=0
UNET DZMax Abort=0
UNET Convert EG Bridges=0
UNET Use Existing IB Tables=0
UNET Froude Limit=0
UNET Froude Power=0
Write IC File=0
Echo Input=False
Echo Output=False
Write Detailed=0

--- CobunCk.f01 (steady flow) ---

Flow Title=NFF Regression Equation
Program Version=4.10
Number of Profiles= 1
Profile Names=P100yr
River Rch & RM=CobunCk,Main            ,34171.4
     966
River Rch & RM=CobunCk,Main            ,32918.9
    1035
River Rch & RM=CobunCk,Main            ,29721.8
    1131
River Rch & RM=CobunCk,Main            ,29316.2
    1304
River Rch & RM=CobunCk,Main            ,26672.1
    1383
River Rch & RM=CobunCk,Main            ,25172.1
    1427
River Rch & RM=CobunCk,Main            ,19716.1
    1521
River Rch & RM=CobunCk,Main            ,18720.6
    2197
River Rch & RM=CobunCk,Main            ,17481.3
    2280
River Rch & RM=CobunCk,Main            ,12574.3
    2443
River Rch & RM=CobunCk,Main            ,7621.5
    2568
River Rch & RM=CobunCk,Main            ,5278.2
    2649
River Rch & RM=CobunCk,Main            ,365.5
    2798
Boundary for River Rch & Prof#=CobunCk,Main            , 1
Up Type= 0
Dn Type= 1
Dn Known WS=907.4
DSS Import GetInterval= 0
DSS Import GetPeak= 0
DSS Import FillOption= 0

--- CobunCk.g01 (geometry) ---

Geom Title=USGS 10m DEM
Program Version=4.10

River Reach=CobunCk         ,Main
Reach XY= 30
     1849601.223      380097.119      1849230.78      380551.729
     1848314.108      380727.661     1847462.387      382685.324
     1847592.057      383494.719     1846955.003      383815.121
     1845990.126      384986.864     1846035.569      386751.146
      1846810.87      387934.808     1846339.045      390920.696
      1847010.06      391936.991     1846370.923      392827.924
     1844756.385       393980.67     1844752.676      394270.062
     1843334.125      394821.031     1843710.514      395000.718
     1843467.632      395750.198     1843610.862      396764.954
     1844209.559      397980.232     1843539.768      398257.142
     1843206.087      397968.947     1842818.066      398103.496
     1843110.601      398798.635     1842710.601      399239.954
     1842892.893       399776.76     1842621.365      400145.857
     1842696.886      401131.621     1840988.898      401474.191
     1840992.804      402420.198      1840367.37      403103.184

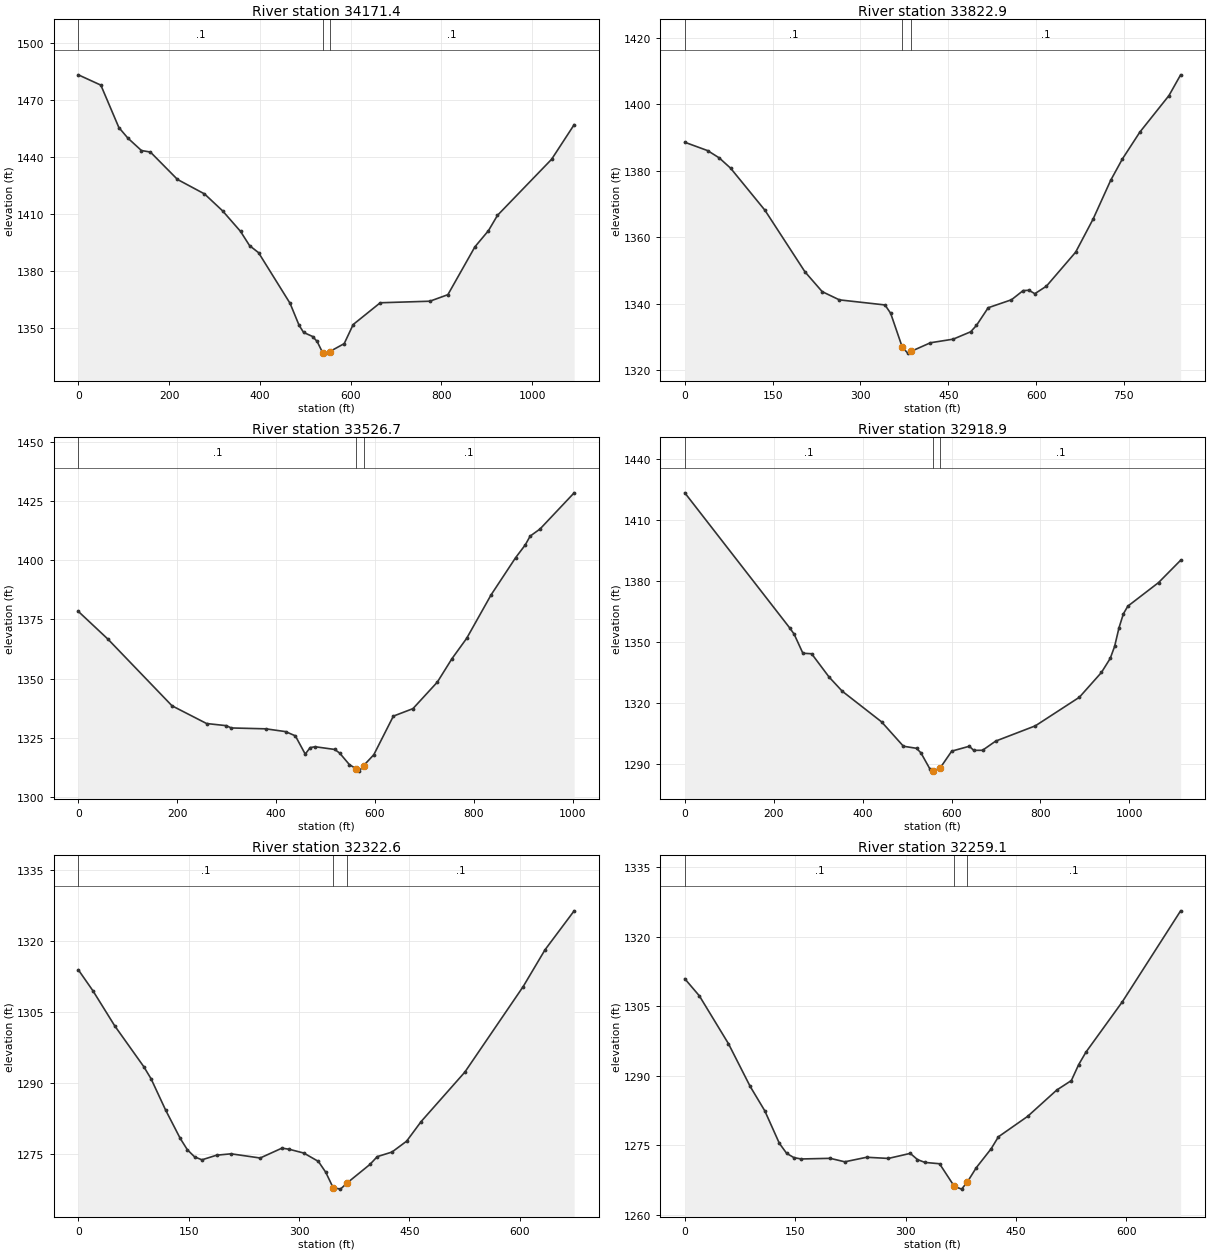
Type RM Length L Ch R = 1 ,34171.4 ,348.4,348.5,349.3
XS GIS Cut Line= 3
     1849313.218      379633.218     1849592.632      380102.237
     1849887.019      380562.474
#Sta/Elev= 30
       0 1483.47    49.6 1478.04    89.3 1455.69   109.2 1450.11     139 1443.58
   158.8 1442.77   218.4 1428.34   277.9 1420.72   317.6 1411.84   357.3 1400.97
   377.2 1393.48     397 1389.75   466.5 1363.03   486.4 1351.43   496.3 1347.72
   516.2 1345.56   526.1 1342.95   538.4 1336.95   545.9 1336.81   553.4 1337.57
   585.7 1341.81   605.5 1351.88   665.1 1363.35   774.4 1364.17   814.1 1367.61
   873.7 1392.84   903.5 1401.35   923.4 1409.43  1042.6 1438.96  1092.3  1457.2
#Mann= 3 , 0 , 0
       0      .1       0   538.4    .045       0   553.4      .1       0
Bank Sta=538.4,553.4
XS Rating Curve= 0 ,0
Exp/Cntr=0.3,0.1

Type RM Length L Ch R = 1 ,33822.9 ,291,296.1,300.4
XS GIS Cut Line= 4
     1849119.748      379966.485     1849267.317      380231.242
     1849351.952      380361.451     1849616.709      380645.739
#Sta/Elev= 30
       0 1388.53    39.1 1386.01    58.7 1383.84    78.2 1380.74   136.9 1368.08
   205.3 1349.55   234.7  1343.6     264 1341.13   341.9  1339.6   351.6  1337.1
   371.5 1326.87   380.8 1325.11   386.5 1325.64   419.6 1328.23   458.4 1329.31
   488.3 1331.53   498.2 1333.45   518.2 1338.76     558 1341.16   577.9 1343.92
   587.9 1344.01   597.9 1342.98   617.8 1345.27   667.6 1355.48   697.5 1365.46
   727.4 1377.07   747.3 1383.47   777.2 1391.57     827 1402.58   846.9 1408.81
#Mann= 3 , 0 , 0
       0      .1       0   371.5    .045       0   386.5      .1       0
Bank Sta=371.5,386.5
XS Rating Curve= 0 ,0
Exp/Cntr=0.3,0.1

Type RM Length L Ch R = 1 ,33526.7 ,613.4,607.8,602
XS GIS Cut Line= 3
     1849019.921      380022.909     1849194.274      380490.487
     1849366.149      380964.445
#Sta/Elev= 30
       0 1378.37    59.9 1366.64   189.6 1338.46   259.5 1330.97   299.4 1330.07
   309.4  1329.1   379.3 1328.73   419.2 1327.56   439.1 1325.77   459.1 1318.04
   469.1  1320.8   479.1 1321.16   518.8 1320.01   528.7 1318.49   548.4 1313.61
   562.3 1311.83   568.2 1310.85   577.3 1313.21   597.9  1317.8   637.4  1334.1
     677 1337.26   726.4 1348.49     756  1358.4   785.7 1366.98   835.1 1385.35
   884.6 1401.03   904.3 1406.49   914.2 1410.21     934 1413.17  1003.2 1428.49
#Mann= 3 , 0 , 0
       0      .1       0   562.3    .045       0   577.3      .1       0
Bank Sta=562.3,577.3
XS Rating Curve= 0 ,0
Exp/Cntr=0.3,0.1

Type RM Length L Ch R = 1 ,32918.9 ,609.7,596.4,583.3
XS GIS Cut Line= 3
     1848322.279      380074.331     1848623.597      380523.665
     1848944.981      380999.579
#Sta/Elev= 30
       0 1423.54   236.1 1356.98   245.9 1353.97   265.6 1344.55   285.3 1344.29
   324.6 1332.81   354.1 1325.86   442.6 1310.76   491.8 1298.74   521.3 1297.73
   531.2 1295.47   550.9 1287.73   559.4 1286.67   560.8 1286.49   574.4 1288.05
   600.4 1296.33     640 1298.74   649.9 1296.72   669.7 1296.75   699.4 1301.29
   788.5 1308.79   887.6 1322.88   937.1 1335.06   956.9 1341.98   966.8  1347.9
   976.7  1357.1   986.6 1363.98   996.5 1367.72  1065.8 1379.37  1115.3 1390.33
#Mann= 3 , 0 , 0
       0      .1       0   559.4    .045       0   574.4      .1       0
Bank Sta=559.4,574.4
XS Rating Curve= 0 ,0
Exp/Cntr=0.3,0.1

Type RM Length L Ch R = 1 ,32322.6 ,63.4,63.5,63.4
XS GIS Cut Line= 4
     1847869.621      380764.793     1848157.815      380895.001
     1848268.927       380940.14     1848478.996      381051.251
#Sta/Elev= 30
       0 1313.92    19.8 1309.49    49.4 1302.07    88.9 1293.42    98.8 1290.86
   118.6 1284.23   138.4 1278.24   148.2 1275.81   158.1  1274.3     168 1273.69
   187.8 1274.66   207.5 1274.96   247.1 1274.07   276.7 1276.16   286.6 1275.92
   306.4 1275.12   326.2 1273.35   336.2 1271.06   346.2  1267.8   356.2 1267.48
   365.6 1268.83   396.2  1272.7   406.2 1274.36   426.2 1275.33   446.1 1277.63
   465.9  1281.8   525.3 1292.27   604.5 1310.37   634.2 1318.16   673.8 1326.41
#Mann= 3 , 0 , 0
       0      .1       0   346.2    .045       0   365.6      .1       0
Bank Sta=346.2,365.6
XS Rating Curve= 0 ,0
Exp/Cntr=0.3,0.1

Type RM Length L Ch R = 1 ,32259.1 ,332,328.2,324.4
XS GIS Cut Line= 4
     1847817.538      380809.931     1848105.732       380940.14
     1848216.843      380985.279     1848426.913       381096.39
#Sta/Elev= 30
       0 1310.93    19.8 1307.24    59.3 1296.92    88.9 1287.67   108.7 1282.42
   128.5  1275.4   138.4 1273.24   148.2 1272.32   158.1 1272.02   197.6 1272.16
   217.4 1271.41   247.1 1272.39   276.7 1272.14   306.4 1273.23   316.2 1271.89
   326.2 1271.28   346.2 1270.99   366.2 1266.12   376.2 1265.51   384.1 1267.09
   396.2 1270.16   416.2  1274.2   426.2 1276.81   465.9 1281.22   505.5 1286.91
   525.3 1288.95   535.2 1292.38   545.1 1295.08   594.6 1305.96   673.8  1325.6
#Mann= 3 , 0 , 0
       0      .1       0   366.2    .045       0   384.1      .1       0
Bank Sta=366.2,384.1
XS Rating Curve= 0 ,0
Exp/Cntr=0.3,0.1

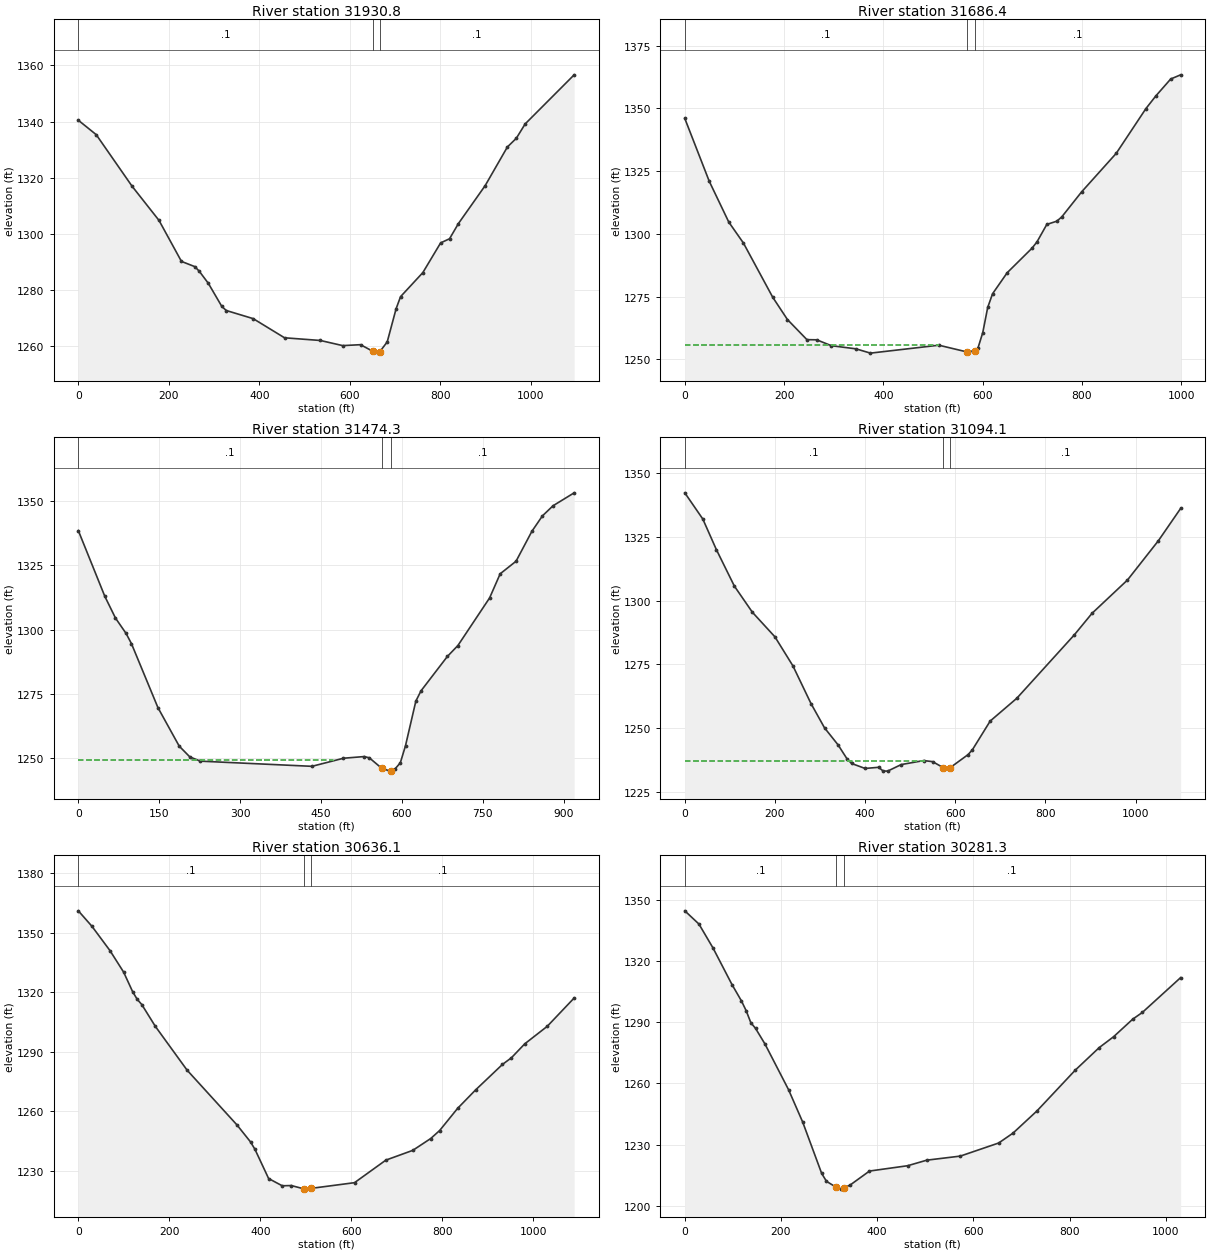
Type RM Length L Ch R = 1 ,31930.8 ,248.3,244.4,240.6
XS GIS Cut Line= 3
      1847379.15      381082.259     1847905.847      381222.885
     1848441.819      381350.845
#Sta/Elev= 30
       0 1340.46    39.6 1335.31   118.9 1316.91   178.4 1304.73     228 1290.11
   257.7 1288.24   267.6 1286.56   287.4  1282.3   317.2 1274.06   327.1  1272.6
   386.6  1269.7   455.9 1262.87   535.2 1261.91   584.5 1260.08   623.9 1260.41
   651.6 1258.01   663.2  1257.4   666.6 1257.93   682.9  1261.4   702.6 1273.26
   712.4 1277.54   761.6 1286.11     801 1296.72   820.7 1298.19   840.3 1303.61
   899.4 1317.13   948.6 1330.93   968.3 1334.02   987.9 1339.15  1096.2 1356.66
#Mann= 3 , 0 , 0
       0      .1       0   651.6    .045       0   666.6      .1       0
Bank Sta=651.6,666.6
XS Rating Curve= 0 ,0
Exp/Cntr=0.3,0.1

Type RM Length L Ch R = 1 ,31686.4 ,205.4,212.1,218.8
XS GIS Cut Line= 4
     1847392.317      381470.392     1847815.494      381474.732
     1848041.189      381489.923     1848386.241      381544.176
#Sta/Elev= 30
       0    1346    49.2 1320.97    88.6 1304.68   118.1 1296.32   177.2 1274.68
   206.7 1265.83     246  1257.8   265.7 1257.74   295.3 1255.39   344.5 1254.15
     374 1252.43   511.7 1255.59   568.8 1252.88   583.8 1253.43   590.4 1254.38
   600.2 1260.64   610.1 1270.63   619.9  1276.1   649.4 1284.49   699.3 1294.26
   709.3 1296.76   729.2 1303.75   749.2 1305.03   759.2 1306.72   799.1 1316.68
     869 1332.09   928.8 1349.93   948.8 1354.98   978.7 1361.72   998.7 1363.39
#Mann= 3 , 0 , 0
       0      .1       0   568.8    .045       0   583.8      .1       0
#XS Ineff= 2 , 0
          511.71 1255.59
Permanent Ineff=
       F       F
Bank Sta=568.8,583.8
XS Rating Curve= 0 ,0
Exp/Cntr=0.3,0.1

Type RM Length L Ch R = 1 ,31474.3 ,378.9,380.2,381.3
XS GIS Cut Line= 4
     1847405.338      381535.496     1847863.237      381652.683
     1848023.827      381715.617     1848284.244      381802.423
#Sta/Elev= 30
       0 1338.54    49.2 1312.93    68.9  1304.5    88.6 1298.51    98.5 1294.56
   147.7 1269.62   187.1 1254.66   206.8 1250.46   226.5 1248.81   433.3  1246.8
   491.8 1249.95   530.2  1250.6   539.7 1250.11   562.5 1246.08   578.1 1244.93
  579.011245.017   587.6 1245.84   597.2 1248.17   606.8 1254.83     626 1272.19
   635.6 1276.19   684.4 1289.55     704 1293.82   762.8 1312.35   782.4 1321.74
   811.8 1326.62   841.2 1338.27   860.8 1344.29   880.4 1348.21   919.6 1353.25
#Mann= 3 , 0 , 0
       0      .1       0   562.5    .045       0  579.01      .1       0
#XS Ineff= 2 , 0
          472.72  1249.1
Permanent Ineff=
       F       F
Bank Sta=562.5,579.01
XS Rating Curve= 0 ,0
Exp/Cntr=0.3,0.1

Type RM Length L Ch R = 1 ,31094.1 ,465.4,458.1,450.5
XS GIS Cut Line= 3
     1847226.582      381748.329     1847713.763      381981.174
     1848223.242      382213.765
#Sta/Elev= 30
       0  1342.3      40 1332.01      70 1320.04     110  1305.7     150 1295.44
     200  1285.8     240 1274.38     280 1259.63     310  1250.1     340 1243.44
     360 1237.92     370 1236.13     400 1234.18     430 1234.63     440 1233.18
     450 1233.13     480  1235.7     530 1237.27   549.8 1236.85   573.7 1234.46
   588.7 1234.49   628.4  1239.6   638.2 1241.55   677.5 1252.77   736.5  1261.7
   864.2 1286.59   903.5 1295.04   982.1  1308.1  1050.9 1323.57    1100 1336.17
#Mann= 3 , 0 , 0
       0      .1       0   573.7    .045       0   588.7      .1       0
#XS Ineff= 2 , 0
          539.41 1237.24
Permanent Ineff=
       F       F
Bank Sta=573.7,588.7
XS Rating Curve= 0 ,0
Exp/Cntr=0.3,0.1

Type RM Length L Ch R = 1 ,30636.1 ,362.7,354.8,346.1
XS GIS Cut Line= 3
     1847067.306      382279.796     1847622.913      382397.005
     1848136.291      382493.207
#Sta/Elev= 30
       0 1361.09    29.9 1353.29    69.7 1340.97    99.6 1330.15   119.5 1320.23
   129.5 1316.41   139.5 1313.79   169.4 1302.75   239.1 1280.68   348.7 1253.05
   378.6 1244.45   388.5 1240.64   418.4 1225.96   448.3 1222.31   468.2 1222.43
   496.5 1220.72   498.1 1220.62   511.5 1220.99   607.3 1223.88   676.2 1235.26
   735.4 1240.19   774.8 1246.16   794.5 1250.21   833.9 1261.37   873.3 1270.65
   932.5 1283.55   952.2 1286.91   981.7 1293.98    1031 1302.79  1090.2 1317.09
#Mann= 3 , 0 , 0
       0      .1       0   496.5    .045       0   511.5      .1       0
Bank Sta=496.5,511.5
XS Rating Curve= 0 ,0
Exp/Cntr=0.3,0.1

Type RM Length L Ch R = 1 ,30281.3 ,550.8,559.5,568.3
XS GIS Cut Line= 4
     1847147.091      382792.006     1847403.168      382724.732
     1847616.149      382675.817     1848162.716      382642.267
#Sta/Elev= 30
       0 1344.49    29.4 1338.02    58.8 1326.24    98.1  1308.4   117.7 1300.42
   127.5 1295.65   137.3 1289.72   147.1 1286.94   166.7  1279.3   215.7 1256.94
   245.2 1241.03   284.6 1215.93   294.6 1212.06     315 1209.14   324.4 1208.25
     330 1208.71   344.2 1210.33     384  1217.1   463.4 1219.71   503.2 1222.43
   572.9 1224.42   652.6 1230.83   682.4 1235.67   732.2 1246.53   811.8 1266.49
   861.6 1277.53   891.5 1282.85   931.3 1291.45   951.2 1294.72  1030.9 1311.79
#Mann= 3 , 0 , 0
       0      .1       0     315    .045       0     330      .1       0
Bank Sta=315,330
XS Rating Curve= 0 ,0
Exp/Cntr=0.3,0.1

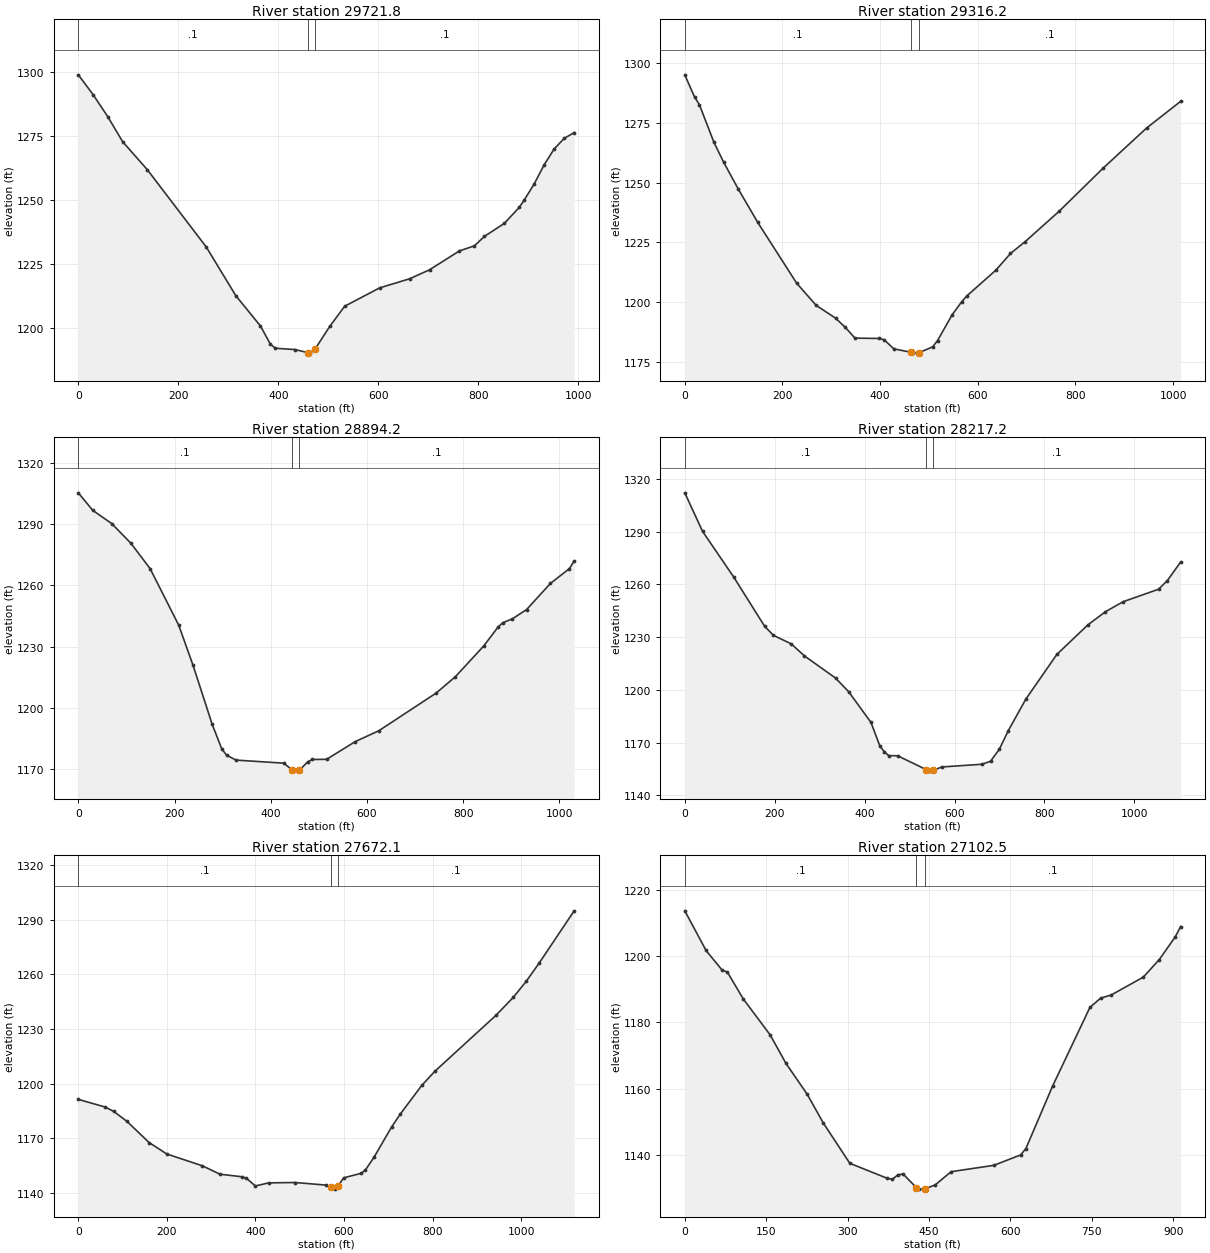
Type RM Length L Ch R = 1 ,29721.8 ,391.5,405.6,418.9
XS GIS Cut Line= 3
     1847235.886      383120.008     1847693.785      383187.282
      1848214.83        383277.4
#Sta/Elev= 30
       0 1298.99    29.5 1291.24    59.1 1282.54    88.6 1272.81   137.9 1261.85
     256 1231.52   315.1 1212.45   364.3 1200.61     384 1193.55   393.9  1191.9
   433.3 1191.39   458.4 1190.21   462.8 1189.99   473.4 1191.57   502.7 1200.42
   532.6 1208.35   602.5 1215.54   662.4  1219.1   702.3 1222.62   762.1 1230.02
   792.1 1232.01     812 1235.68   851.9 1240.79   881.8 1247.08   891.8 1249.96
   911.8 1256.32   931.7 1263.78   951.7 1269.98   971.6 1274.07   991.6 1276.37
#Mann= 3 , 0 , 0
       0      .1       0   458.4    .045       0   473.4      .1       0
Bank Sta=458.4,473.4
XS Rating Curve= 0 ,0
Exp/Cntr=0.3,0.1

Type RM Length L Ch R = 1 ,29316.2 ,415.2,422,429.2
XS GIS Cut Line= 3
     1847177.726      383222.439     1847533.843      383540.941
     1847942.577      383890.082
#Sta/Elev= 30
       0 1295.09    19.9 1285.85    29.9 1282.61    59.7 1266.85    79.6 1258.53
   109.5 1247.33   149.3 1233.39   228.9    1208   268.7 1198.73   308.6 1193.34
   328.5 1189.52   348.4 1184.97   398.1 1184.83   408.1 1184.31     428  1180.5
   462.3 1179.09   467.8  1178.7  479.341178.846   507.6 1181.34   517.6 1183.98
   547.4 1194.71   567.4 1200.28   577.3 1202.58     637  1213.4   666.9 1220.37
   696.8  1225.3   766.4    1238     856 1255.94   945.6 1272.84  1015.3 1283.99
#Mann= 3 , 0 , 0
       0      .1       0   462.3    .045       0  479.34      .1       0
Bank Sta=462.3,479.34
XS Rating Curve= 0 ,0
Exp/Cntr=0.3,0.1

Type RM Length L Ch R = 1 ,28894.2 ,683.4,676.9,668.8
XS GIS Cut Line= 3
     1846947.826      383351.318     1847156.752      383689.513
     1847485.351      384231.033
#Sta/Elev= 30
       0 1305.39    29.8 1296.84    69.6 1290.28   109.3 1280.67   149.1 1268.28
   208.7 1240.52   238.5 1220.84   278.3 1191.89   298.1 1179.94   308.1 1176.78
     328 1174.35   427.2 1172.86   444.1 1169.59   456.9 1168.95   459.1 1169.28
   476.7 1173.44   486.6 1174.66   516.3 1174.74   575.7 1183.42   625.2  1188.8
   743.9 1207.21   783.5 1215.13   842.9 1230.32   872.6 1239.55   882.5  1241.7
   902.3  1243.6     932 1248.16   981.5 1260.96    1021 1268.23  1030.9 1272.01
#Mann= 3 , 0 , 0
       0      .1       0   444.1    .045       0   459.1      .1       0
#XS Ineff= 2 , 0
          427.07 1172.85
Permanent Ineff=
       F       F
Bank Sta=444.1,459.1
XS Rating Curve= 0 ,0
Exp/Cntr=0.3,0.1

Type RM Length L Ch R = 1 ,28217.2 ,546.6,545.2,546.3
XS GIS Cut Line= 3
     1846368.109      383816.513     1846777.795      384186.749
     1847216.409       384519.67
#Sta/Elev= 30
       0 1312.04    39.4 1290.16   108.5 1264.26   177.5 1236.16   197.2 1230.98
   236.6 1226.16   266.2 1219.27   335.3 1206.69   364.8 1198.82   414.1 1181.45
   433.9 1168.02   443.7 1164.76   453.6 1162.58   473.3  1162.5   537.4 1154.58
   542.3 1153.76   552.4 1154.23   571.9 1156.14   660.4 1157.65     680 1159.36
   699.7 1166.26   719.4 1176.74   758.7 1194.78   827.5 1220.13   896.4 1236.92
   935.7 1244.44     975 1250.12  1053.7 1257.21  1073.4 1262.16  1102.8 1272.69
#Mann= 3 , 0 , 0
       0      .1       0   537.4    .045       0   552.4      .1       0
Bank Sta=537.4,552.4
XS Rating Curve= 0 ,0
Exp/Cntr=0.3,0.1

Type RM Length L Ch R = 1 ,27672.1 ,569.1,569.6,567
XS GIS Cut Line= 3
     1845984.583      384241.813     1846472.066      384555.299
     1846886.667      384901.395
#Sta/Elev= 30
       0  1191.3      60 1187.13    79.9 1184.69   109.9 1179.19   159.9 1167.54
   199.9 1161.27   279.8 1154.82   319.8 1150.17   369.7 1148.76   379.7 1147.92
   399.7 1143.71   429.7  1145.4   489.6 1145.61   559.6 1144.18   569.6  1142.9
   579.6 1141.97   587.1 1143.91   599.2 1148.18   638.5 1150.65   648.3  1152.5
     668 1159.64   707.2 1176.04   726.9 1183.21     776 1199.11   805.4 1206.82
   942.9 1237.46   982.2  1247.4  1011.6 1256.26  1041.1  1266.4  1119.6 1294.93
#Mann= 3 , 0 , 0
       0      .1       0   569.6    .045       0   587.1      .1       0
Bank Sta=569.6,587.1
XS Rating Curve= 0 ,0
Exp/Cntr=0.3,0.1

Type RM Length L Ch R = 1 ,27102.5 ,443.5,430.4,419.3
XS GIS Cut Line= 3
     1845704.636      384615.234     1846005.405      384867.208
     1846438.143      385157.769
#Sta/Elev= 30
       0 1213.69    39.2 1201.72    68.7 1195.81    78.5 1195.19   107.9 1187.06
     157 1176.32   186.4 1167.66   225.6 1158.32     255 1149.72   304.1  1137.5
   372.8 1132.99   382.6 1132.68   392.4 1134.01   402.2 1134.28   426.8 1130.16
   431.7 1129.71   441.8 1129.75   461.2 1130.96   490.7 1134.97   569.4 1136.89
   618.6 1140.01   628.4 1141.92   677.6 1160.77   746.4 1184.52   766.1 1187.34
   785.8  1188.3   844.8 1193.68   874.3 1198.99   903.8 1205.86   913.6 1208.96
#Mann= 3 , 0 , 0
       0      .1       0   426.8    .045       0   441.8      .1       0
#XS Ineff= 2 , 0
          402.22 1134.24
Permanent Ineff=
       F       F
Bank Sta=426.8,441.8
XS Rating Curve= 0 ,0
Exp/Cntr=0.3,0.1

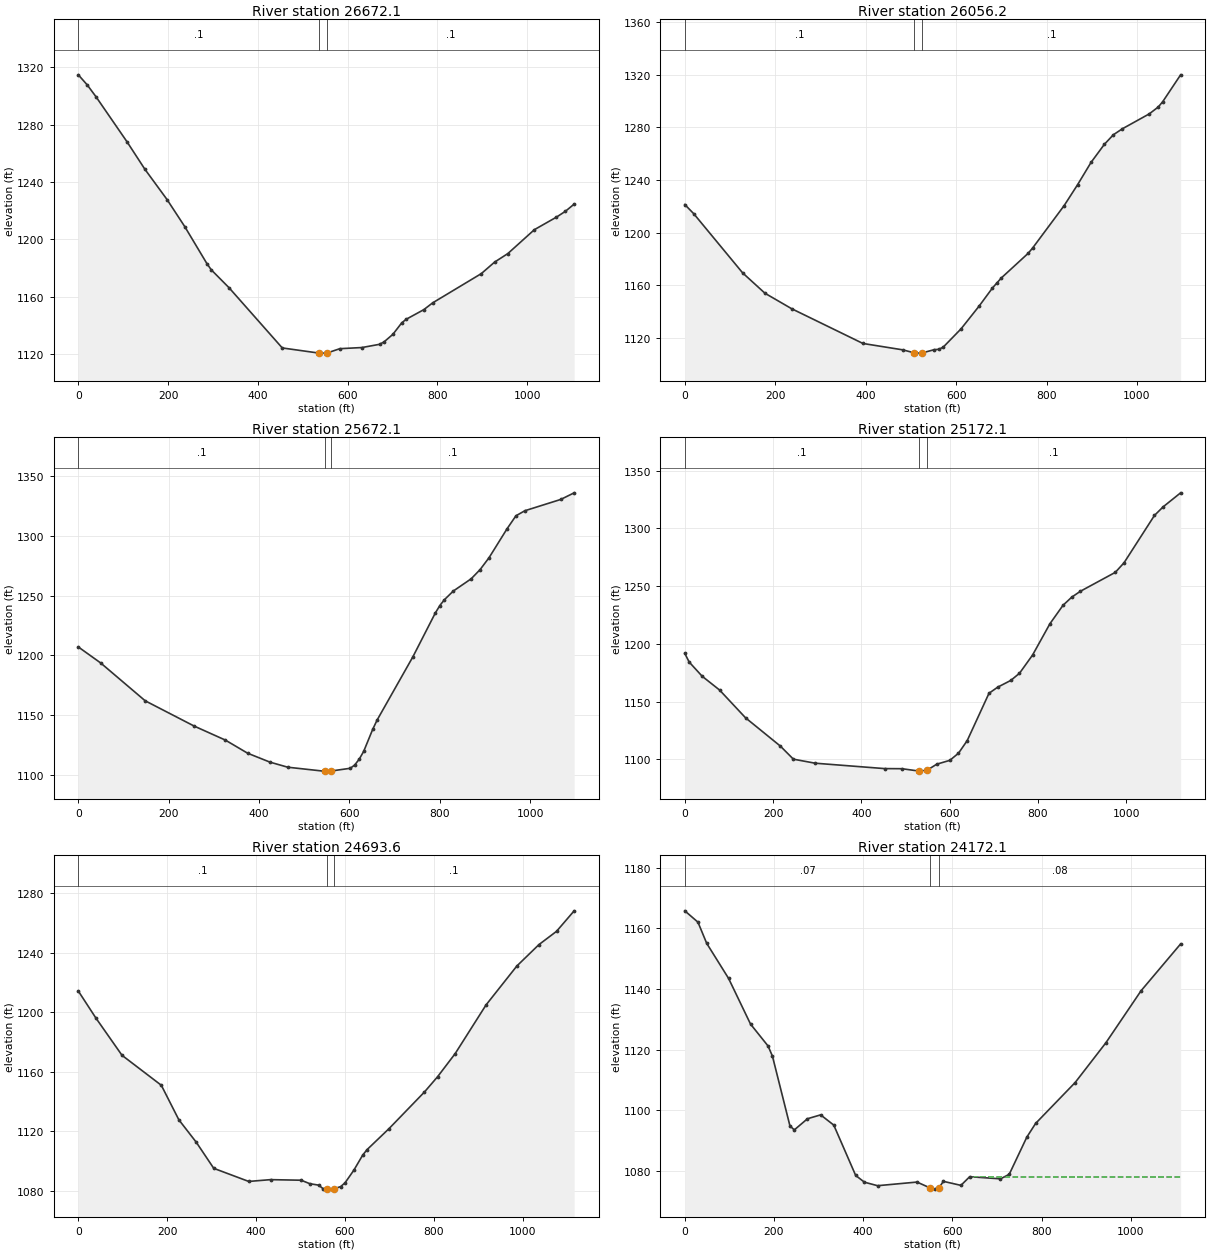
Type RM Length L Ch R = 1 ,26672.1 ,615.3,615.8,614.4
XS GIS Cut Line= 3
     1845411.907       385290.75     1845955.004      385304.059
     1846513.076      385366.239
#Sta/Elev= 30
       0 1314.86    19.8 1307.83    39.5 1299.51   108.6 1268.08   148.2 1249.02
   197.6 1227.86   237.1 1208.97   286.4 1183.18   296.3 1178.76   335.8  1166.3
   454.4 1124.28   535.8  1120.7   550.8 1120.66  553.481120.683   582.7 1123.76
   631.9 1124.56   671.3 1126.82   681.2 1128.51   700.9 1133.78   720.6 1141.78
   730.4 1144.26   769.8    1151   789.5 1155.74   897.9 1176.14   927.5 1184.17
     957 1190.12  1016.1 1206.79  1065.4 1215.57  1085.1 1219.59  1104.8 1224.65
#Mann= 3 , 0 , 0
       0      .1       0   535.8    .045       0  553.48      .1       0
Bank Sta=535.8,553.48
XS Rating Curve= 0 ,0
Exp/Cntr=0.3,0.1

Type RM Length L Ch R = 1 ,26056.2 ,390.4,384.2,381
XS GIS Cut Line= 3
     1845449.365      385887.262     1846000.257      385913.959
     1846536.742      386010.054
#Sta/Elev= 30
       0 1221.41    19.7 1214.48     128  1169.5   177.3 1154.08   236.4 1142.32
     394 1115.95   482.6 1111.08   507.2 1108.85   512.1 1108.62  524.491108.734
   551.5 1111.23   561.4 1111.51   571.4 1113.11     611 1127.06   650.6 1144.18
   680.4 1158.05   690.3  1161.9   700.2 1165.73   759.6 1184.44   769.6 1188.56
   838.9 1220.56   868.6  1236.4   898.4 1253.36   928.1 1267.18   947.9 1274.39
   967.7  1278.9  1027.2 1290.22    1047 1295.41  1056.9 1299.43  1096.6 1319.87
#Mann= 3 , 0 , 0
       0      .1       0   507.2    .045       0  524.49      .1       0
Bank Sta=507.2,524.49
XS Rating Curve= 0 ,0
Exp/Cntr=0.3,0.1

Type RM Length L Ch R = 1 ,25672.1 ,511.9,500,491.2
XS GIS Cut Line= 3
      1845455.73      386411.416     1845993.067       386284.18
     1846535.493      386232.246
#Sta/Elev= 30
       0 1207.09    49.3 1193.77   147.9 1162.11   256.4 1140.96   325.4 1129.25
   374.7 1118.27     424 1110.84   463.4 1106.59   542.3 1103.32   544.7 1103.33
   559.7 1103.44   601.7  1105.7   611.6 1108.46   621.6 1113.37   631.4 1119.84
   651.3  1138.2   661.2 1146.08   740.4 1198.96     790 1235.58   799.9 1241.69
   809.8 1246.51   829.6 1253.81   869.2 1264.06     889 1271.77   908.9 1281.77
   948.5 1305.81   968.3 1316.73   988.1 1320.96  1067.4 1330.39  1097.1 1335.92
#Mann= 3 , 0 , 0
       0      .1       0   544.7    .045       0   559.7      .1       0
Bank Sta=544.7,559.7
XS Rating Curve= 0 ,0
Exp/Cntr=0.3,0.1

Type RM Length L Ch R = 1 ,25172.1 ,473.8,478.4,476.8
XS GIS Cut Line= 3
     1845659.285      387137.855     1846057.817      386771.838
     1846573.827      386502.364
#Sta/Elev= 30
       0 1191.67     9.8 1184.24    39.4 1171.86    78.7 1159.97   137.7 1135.85
   216.4 1111.41     246 1100.05   295.2 1096.57   452.6 1091.89   491.9  1091.8
   531.3  1089.7   548.6 1090.41   570.7 1095.71   600.3 1099.03     620  1105.2
   639.8 1116.17   689.1 1157.13   708.8 1162.42   738.4 1168.25   758.2 1174.46
   787.8 1190.24   827.2  1217.4   856.8 1233.34   876.6  1240.4   896.3 1245.52
   975.2 1261.86     995 1270.15    1064 1311.21  1083.8 1318.68  1123.2 1330.75
#Mann= 3 , 0 , 0
       0      .1       0   531.3    .045       0   548.6      .1       0
Bank Sta=531.3,548.6
XS Rating Curve= 0 ,0
Exp/Cntr=0.3,0.1

Type RM Length L Ch R = 1 ,24693.6 ,517,521.6,528.3
XS GIS Cut Line= 3
      1845826.37       387545.85      1846237.44      387194.356
     1846727.499      386893.308
#Sta/Elev= 30
       0 1214.36    39.3 1196.32    98.3 1171.15   186.8 1150.98   226.2 1127.79
   265.5 1112.64   304.8 1095.11   383.5 1086.29   432.7  1087.5   501.5 1087.11
   521.2 1084.76   540.9 1083.81   550.8 1081.43   559.7 1081.15   560.7 1081.12
   574.7 1081.27   590.4  1082.8   600.4  1085.4   620.2 1093.89     640 1103.98
   649.9  1107.7   699.5 1121.88   778.8 1146.38   808.6 1156.73   848.3 1172.34
   917.7 1205.04   987.1 1231.25  1036.7 1245.61  1076.3 1254.54    1116 1268.34
#Mann= 3 , 0 , 0
       0      .1       0   559.7    .045       0   574.7      .1       0
Bank Sta=559.7,574.7
XS Rating Curve= 0 ,0
Exp/Cntr=0.3,0.1

Type RM Length L Ch R = 1 ,24172.1 ,537.1,548.1,556.3
XS GIS Cut Line= 3
     1846057.291      387774.677     1846578.588      387569.997
     1847110.907      387424.432
#Sta/Elev= 30
       0 1165.77    29.5 1162.03    49.1 1155.05    98.2 1143.47   147.4 1128.41
   186.7 1121.18   196.5 1117.85   235.8 1094.82   245.6  1093.5   275.1 1097.18
   304.6 1098.46   334.1 1095.08   383.2 1078.48   402.8 1076.25   432.3 1075.09
   520.7 1076.29   550.2 1074.35     560 1073.96   569.9 1074.37   579.8 1076.53
   619.2  1075.2   638.9 1078.06   707.9 1077.35   727.6 1078.86     767 1091.11
   786.7 1095.63   875.4 1109.13   944.4 1122.26  1023.2  1139.4  1111.9 1154.85
#Mann= 3 , 0 , 0
       0     .07       0   550.2    .045       0   569.9     .08       0
#XS Ineff= 2 , 0
                          644.31         1078.08
Permanent Ineff=
       F       F
Bank Sta=550.2,569.9
XS Rating Curve= 0 ,0
Exp/Cntr=0.3,0.1

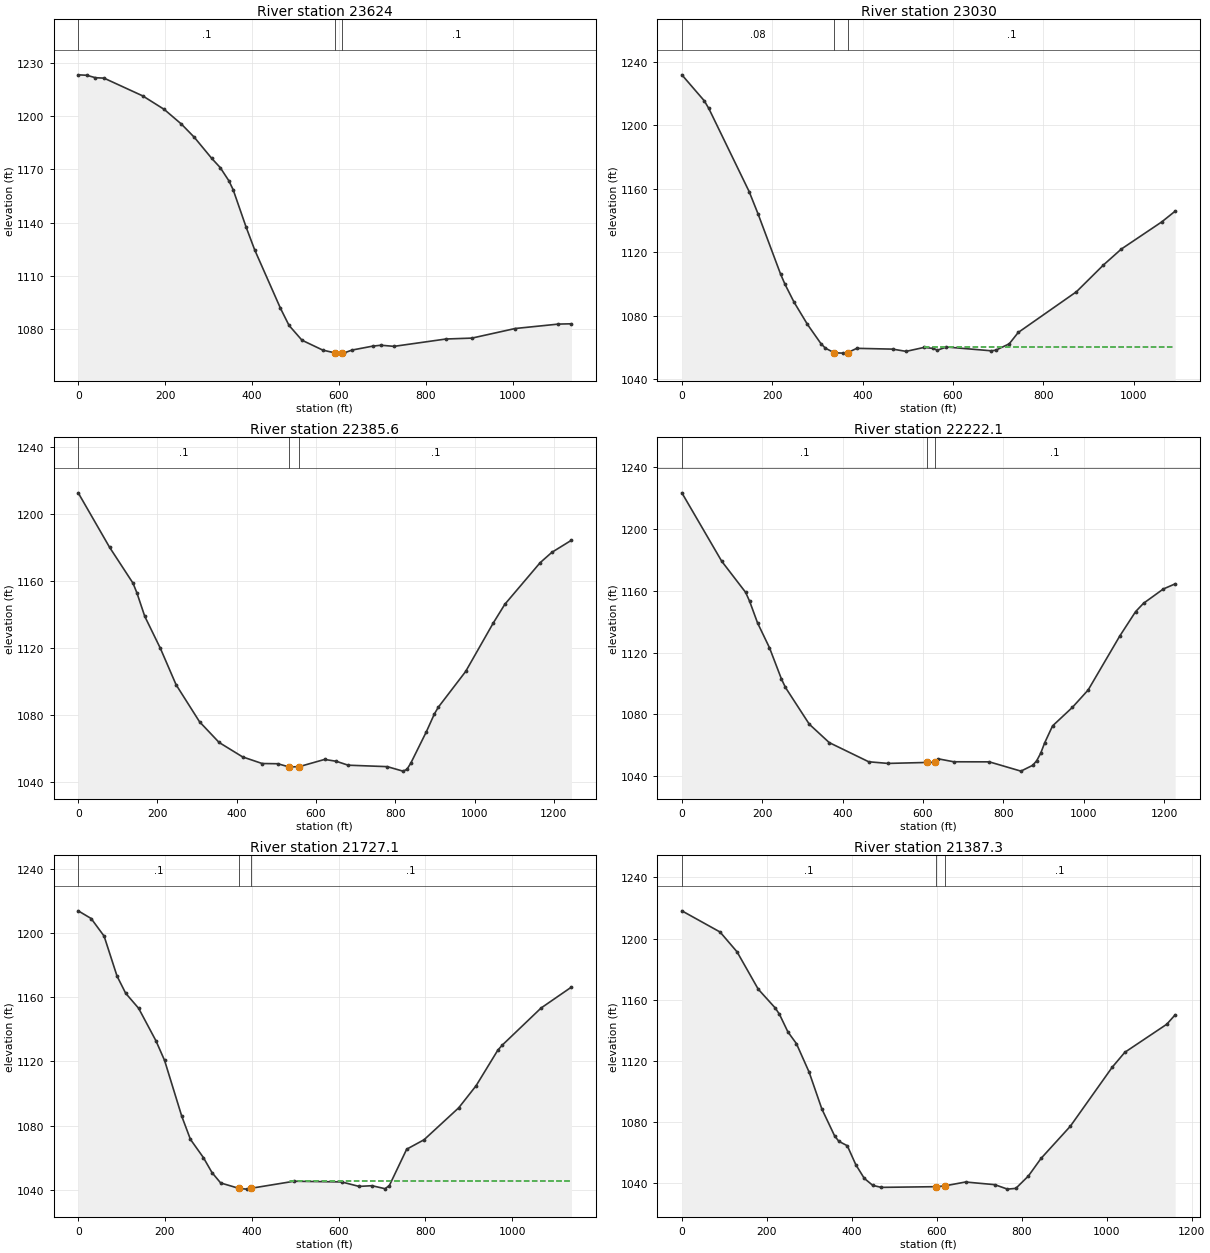
Type RM Length L Ch R = 1 ,23624   ,590.7,594,597.3
XS GIS Cut Line= 4
     1846196.583      388094.441     1846717.223      388028.645
     1846889.153      388034.607     1847323.787      388090.946
#Sta/Elev= 30
       0 1223.08    19.8 1222.83    39.6 1221.46    59.4 1221.22   148.5 1211.23
     198 1203.62   237.6 1195.35   267.3 1187.91     307 1176.16   326.8 1170.91
   346.6 1163.52   356.5  1158.5   386.2 1137.55     406 1124.68   465.4 1091.79
   485.2 1082.11   514.9 1073.81     563 1068.22     592 1066.61     607 1066.55
   610.8 1066.54   629.9 1068.25   677.7 1070.48   696.8 1070.98   726.7 1070.35
   846.2 1074.48     906 1074.99  1005.6 1080.39  1105.2 1082.88  1135.1 1083.04
#Mann= 3 , 0 , 0
       0      .1       0     592    .045       0     607      .1       0
#XS Ineff= 2 , 0
                          696.49         1070.91
Permanent Ineff=
       F       F
Bank Sta=592,607
XS Rating Curve= 0 ,0
Exp/Cntr=0.3,0.1

Type RM Length L Ch R = 1 ,23030   ,648.9,644.4,639.5
XS GIS Cut Line= 3
     1846307.586      388545.653     1846844.882      388642.754
     1847382.179      388739.856
#Sta/Elev= 30
       0 1231.86    49.6  1215.5    59.6 1210.69   148.9 1158.34   168.8 1144.16
   218.4 1106.44   228.3 1099.93   248.2 1088.74     278 1074.67   307.8 1062.58
   317.7  1059.7   337.5 1056.75   357.4 1056.56   367.3 1056.92   387.2 1059.58
   466.6 1059.08   496.4 1057.67   536.1 1060.15   555.9 1059.54   565.8 1058.42
   585.7 1060.41     685 1058.03   694.9  1058.4   724.7 1062.41   744.6 1069.57
   873.6 1095.25   933.2 1112.06   972.9 1122.12  1062.2 1139.19    1092 1145.97
#Mann= 3 , 0 , 0
       0     .08       0   337.5    .045       0   367.3      .1       0
#XS Ineff= 2 , 0
                          535.52         1060.38
Permanent Ineff=
       F       F
Bank Sta=337.5,367.3
XS Rating Curve= 0 ,0
Exp/Cntr=0.3,0.1

Type RM Length L Ch R = 1 ,22385.6 ,146,163.5,181.1
XS GIS Cut Line= 4
     1846192.894      389164.416     1846621.821      389234.768
     1846798.786      389227.558     1847431.633      389218.315
#Sta/Elev= 30
       0 1212.86      79 1180.36   138.3 1158.82   148.2 1152.98   167.9 1139.02
   207.4 1119.83     247 1098.09   306.2 1075.94   355.6 1063.56   414.9 1054.93
   464.2 1050.98   503.5 1050.85  531.881048.957   557.3 1049.09   621.7 1053.42
   651.3 1052.32     681 1049.98   779.9 1049.11   819.4 1046.43   829.3 1047.44
   839.2 1051.17   878.8 1070.12   898.6 1080.54   908.4 1084.57   977.7 1106.04
  1046.9 1134.84  1076.6 1146.23  1165.6 1171.08  1195.2 1177.27  1244.7 1184.52
#Mann= 3 , 0 , 0
       0      .1       0  531.88    .045       0   557.3      .1       0
#XS Ineff= 2 , 0
                          622.07         1053.34
Permanent Ineff=
       F       F
Bank Sta=531.88,557.3
XS Rating Curve= 0 ,0
Exp/Cntr=0.3,0.1

Type RM Length L Ch R = 1 ,22222.1 ,510.7,494.9,477.2
XS GIS Cut Line= 4
     1846171.713      389207.819     1846604.005      389265.111
     1846789.769      389432.646     1847307.998      389588.896
#Sta/Elev= 30
       0 1223.36    99.1 1179.13   158.6 1158.98   168.5 1153.28   188.3 1139.22
     218 1123.15   247.8 1102.91   257.7 1097.47   317.1 1073.66   366.7 1061.76
   464.9 1049.36     513 1048.29   609.2 1048.91   629.2 1049.04   638.1 1051.25
   676.6 1049.35     765  1049.3   843.7  1043.3   873.2 1047.09     883 1050.05
   892.9 1054.85   902.7 1061.52   922.4 1072.55   971.6  1084.5    1011 1095.78
  1089.7 1130.71  1129.1  1146.5  1148.8 1151.89    1198 1161.13  1227.5 1164.46
#Mann= 3 , 0 , 0
       0      .1       0   609.2    .045       0   629.2      .1       0
#XS Ineff= 2 , 0
                          638.49          1051.2
Permanent Ineff=
       F       F
Bank Sta=609.2,629.2
XS Rating Curve= 0 ,0
Exp/Cntr=0.3,0.1

Type RM Length L Ch R = 1 ,21727.1 ,331.3,339.8,348.1
XS GIS Cut Line= 3
     1846194.327      389665.346     1846731.402      389655.054
      1847328.23      389713.044
#Sta/Elev= 30
       0  1213.8    29.8 1209.02    59.7 1198.04    89.5 1173.15   109.4 1162.48
   139.3 1153.09   179.1 1132.91     199 1120.69   238.7 1085.86   258.6 1071.52
   288.5 1060.16   308.4 1050.79   328.3 1044.36  371.261040.915     388 1040.51
   397.9 1041.02   497.4 1045.42   607.1 1044.99   647.1 1042.21   677.1 1042.64
   707.1 1040.77   717.1 1042.75     757 1065.37     797 1071.25     877 1091.17
     917 1104.91   966.9 1126.98   976.9 1130.08  1066.8  1153.3  1136.8 1166.33
#Mann= 3 , 0 , 0
       0      .1       0  371.26    .045       0   397.9      .1       0
#XS Ineff= 2 , 0
                          488.55         1045.31
Permanent Ineff=
       F       F
Bank Sta=371.26,397.9
XS Rating Curve= 0 ,0
Exp/Cntr=0.3,0.1

Type RM Length L Ch R = 1 ,21387.3 ,717.4,723.5,729.3
XS GIS Cut Line= 3
      1846095.12      389749.361     1846605.689      389951.575
     1847184.475      390149.927
#Sta/Elev= 30
       0  1218.2    89.9 1204.35   129.8 1191.41   179.7 1166.99   219.7 1154.69
   229.6 1150.61   249.6 1139.02   269.6 1131.38   299.5 1112.73   329.5 1088.62
   359.4 1071.12   369.4 1067.51   389.4 1064.59   409.4  1052.2   429.3 1043.29
   449.3 1038.68   469.3 1037.38   598.5 1037.83   618.2 1038.32   667.6 1040.89
   736.6 1039.14   766.3 1036.23     786 1036.72   815.6 1044.81   845.2 1056.26
   914.3 1077.35    1013 1115.99  1042.6  1125.7  1141.2 1144.03    1161 1150.18
#Mann= 3 , 0 , 0
       0      .1       0   598.5    .045       0   618.2      .1       0
#XS Ineff= 2 , 0
                          667.88         1040.85
Permanent Ineff=
       F       F
Bank Sta=598.5,618.2
XS Rating Curve= 0 ,0
Exp/Cntr=0.3,0.1