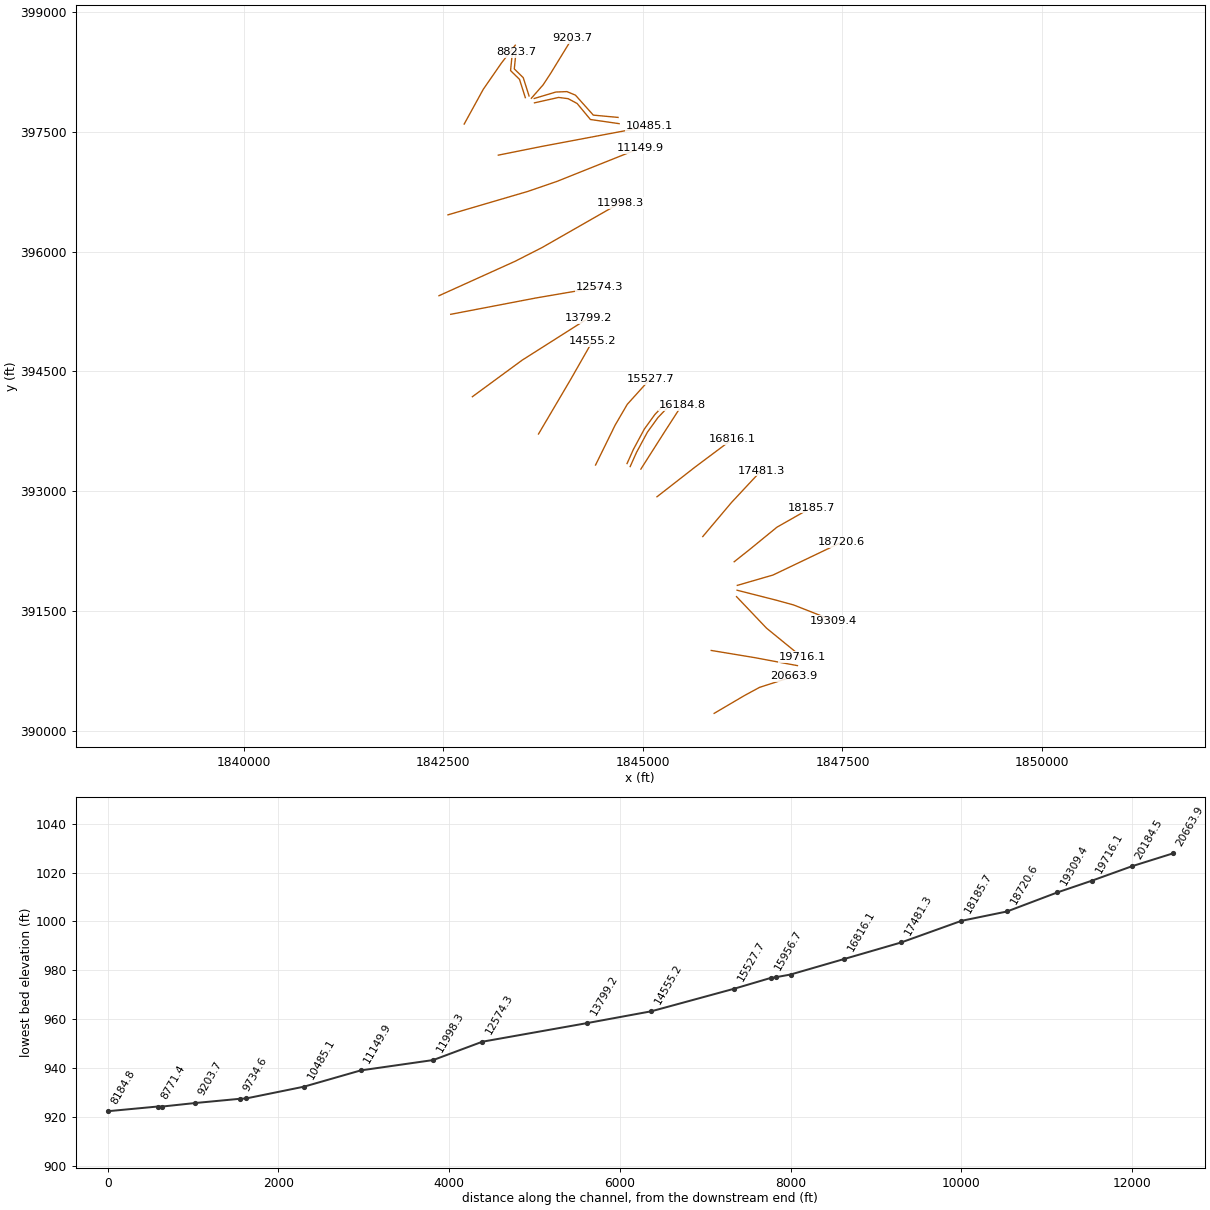
HEC-RAS study CobunCk.prj: CobunCk

--- CobunCk.g01 (geometry) --- (continued)

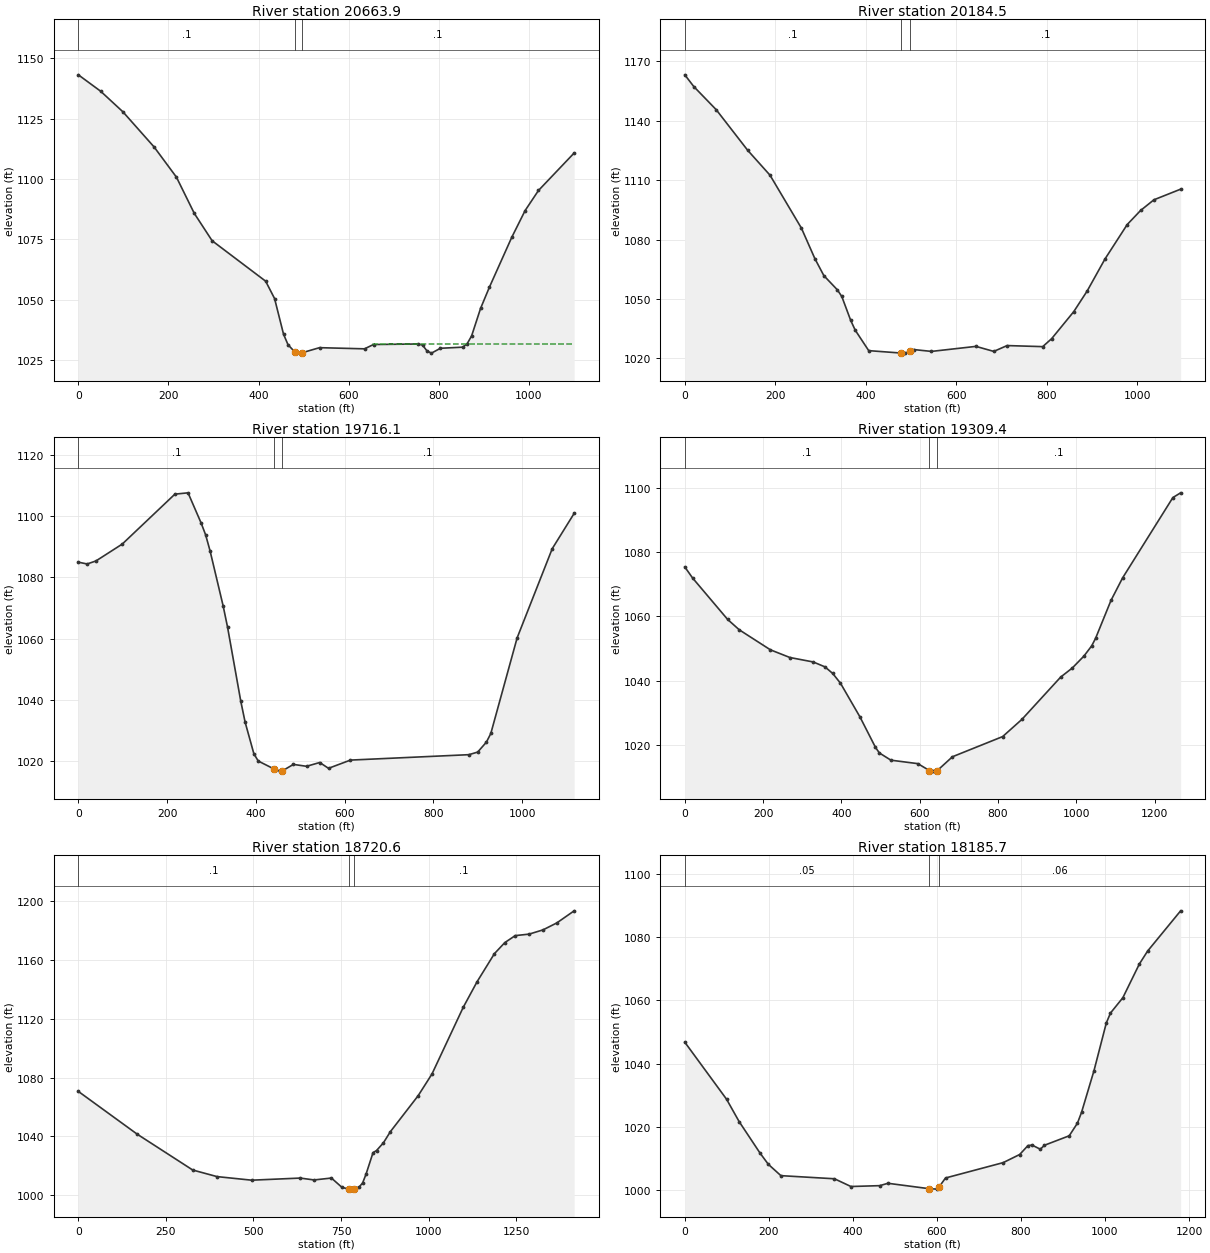
Type RM Length L Ch R = 1 ,20663.9 ,494.1,479.3,461.3
XS GIS Cut Line= 4
     1845893.004      390220.486     1846277.119       390446.18
     1846461.581      390546.006     1846885.676      390682.028
#Sta/Elev= 30
       0 1143.11    49.5 1136.32      99 1127.78   168.3  1113.2   217.8 1100.71
   257.4 1085.71     297 1074.37   415.8 1057.62   435.6 1050.43   455.5 1035.66
   465.5 1031.28   480.1 1028.39  496.771027.985   535.4 1030.08   635.3  1029.6
   655.2 1031.39   754.2  1031.6   764.1 1031.14     774 1028.72   783.9 1027.82
   803.7 1029.83   853.2 1030.29   863.1 1031.71     873 1034.97   892.8 1046.31
   912.6 1055.19   962.1  1075.8   991.8  1086.9  1021.4  1095.2  1100.6 1110.73
#Mann= 3 , 0 , 0
       0      .1       0   480.1    .045       0  496.77      .1       0
#XS Ineff= 2 , 0
                          654.92         1031.54
Permanent Ineff=
       F       F
Bank Sta=480.1,496.77
XS Rating Curve= 0 ,0
Exp/Cntr=0.3,0.1

Type RM Length L Ch R = 1 ,20184.5 ,483.1,468.5,453.7
XS GIS Cut Line= 3
     1845856.961      391007.885     1846394.821      390919.083
     1846936.045      390818.171
#Sta/Elev= 30
       0 1163.26    19.8 1157.35    69.4 1145.64   138.8 1125.16   188.3 1112.52
   257.7 1085.76   287.4 1070.37   307.3 1061.75     337  1054.6   346.9 1051.22
   366.7 1039.08   376.6 1034.18   406.4 1023.83  478.721022.592   485.7 1022.57
   497.7  1023.4   505.5 1024.38   545.1 1023.44   643.4 1025.98   682.8 1023.44
   712.3 1026.39   790.9 1025.85   810.6 1029.86   859.7 1043.59   889.2 1053.99
   928.6 1070.18   977.7 1087.58  1007.2 1094.68  1036.7 1100.09  1095.7 1105.45
#Mann= 3 , 0 , 0
       0      .1       0  478.72    .045       0   497.7      .1       0
Bank Sta=478.72,497.7
XS Rating Curve= 0 ,0
Exp/Cntr=0.3,0.1

Type RM Length L Ch R = 1 ,19716.1 ,391.1,406.6,420.5
XS GIS Cut Line= 3
     1846173.257      391681.598     1846548.121      391287.514
     1846992.584      390925.337
#Sta/Elev= 30
       0 1085.01    19.8 1084.42    39.6  1085.4    98.9 1090.92   217.6 1107.26
   247.2 1107.69   276.9 1097.74   286.8 1093.95   296.7 1088.78   326.3  1070.7
   336.2 1063.77   365.9 1039.62   375.8 1032.68   395.6 1022.31   405.4 1019.96
   441.41017.333   454.9 1016.66   459.1  1016.7   484.6 1018.86   514.2 1018.24
   543.9 1019.48   563.7 1017.58   613.1 1020.27     880 1022.04   899.8 1022.89
   919.5 1026.15   929.4 1028.97   988.7 1060.24  1067.8 1089.42  1117.2 1100.97
#Mann= 3 , 0 , 0
       0      .1       0   441.4    .045       0   459.1      .1       0
Bank Sta=441.4,459.1
XS Rating Curve= 0 ,0
Exp/Cntr=0.3,0.1

Type RM Length L Ch R = 1 ,19309.4 ,574.8,588.8,604.2
XS GIS Cut Line= 4
     1846179.897      391761.718     1846661.667      391639.322
      1846888.99       391576.99     1847385.626       391381.51
#Sta/Elev= 30
       0 1075.43    19.9 1071.98   109.4 1059.08   139.2 1055.84   218.7 1049.61
   268.4 1047.22   328.1 1045.83   357.9 1044.31   377.8 1042.26   397.7  1039.2
   447.4 1028.72   487.1 1019.22   497.1 1017.48   526.5 1015.24   595.3 1014.16
   624.8 1012.01   634.6 1011.83   644.4 1011.94   683.7 1016.31   811.9 1022.59
   861.3 1027.97   960.1 1041.12   989.8 1043.95  1019.4 1047.65  1039.2 1050.82
  1049.1 1053.14  1088.6 1064.99  1118.2    1072  1246.7 1097.03  1266.5 1098.51
#Mann= 3 , 0 , 0
       0      .1       0   624.8    .045       0   644.4      .1       0
Bank Sta=624.8,644.4
XS Rating Curve= 0 ,0
Exp/Cntr=0.3,0.1

Type RM Length L Ch R = 1 ,18720.6 ,528.1,534.9,540.5
XS GIS Cut Line= 3
      1846183.55      391822.388     1846630.417      391951.822
     1847488.237      392361.451
#Sta/Elev= 30
       0 1070.61   168.3 1041.44   326.6 1017.06     396 1012.57   494.9 1010.13
   633.6 1011.57   673.2 1010.29   722.7 1011.59   752.4 1005.32   771.5 1004.06
   782.1 1004.04   786.5  1004.4   801.9  1005.5   811.8 1008.26   821.7 1014.35
   841.5 1028.91   851.4  1030.3   871.2  1035.6     891 1043.17   970.2 1067.63
  1009.8 1082.46    1099 1127.86  1138.6 1145.31  1188.1 1164.44  1217.8 1171.97
  1247.5 1176.72  1287.1 1177.74  1326.7 1180.62  1366.3 1185.37  1415.8 1193.61
#Mann= 3 , 0 , 0
       0      .1       0   771.5    .045       0   786.5      .1       0
Bank Sta=771.5,786.5
XS Rating Curve= 0 ,0
Exp/Cntr=0.3,0.1

Type RM Length L Ch R = 1 ,18185.7 ,702,704.5,706.8
XS GIS Cut Line= 4
     1846143.874      392117.864     1846338.751      392272.135
     1846679.897      392550.781      1847106.98      392792.968
#Sta/Elev= 30
       0 1046.75    99.4 1028.68   129.2 1021.62     179 1011.63   198.8 1008.06
   228.7 1004.47   356.2 1003.48   395.4 1001.03   463.9  1001.3   483.5 1002.05
   581.4 1000.34   600.9  1000.2  604.371000.752   620.5 1003.73   757.8  1008.6
     797 1011.17   816.7    1014   826.5 1014.15   846.1 1012.84     856  1014.1
   914.9  1017.1   934.5 1021.11   944.3 1024.57   973.8 1037.72  1003.2 1052.87
  1013.1 1055.99  1042.5 1060.84  1081.8 1071.53  1101.4 1075.62    1180 1088.37
#Mann= 3 , 0 , 0
       0     .05       0   581.4    .045       0  604.37     .06       0
Bank Sta=581.4,604.37
XS Rating Curve= 0 ,0
Exp/Cntr=0.3,0.1

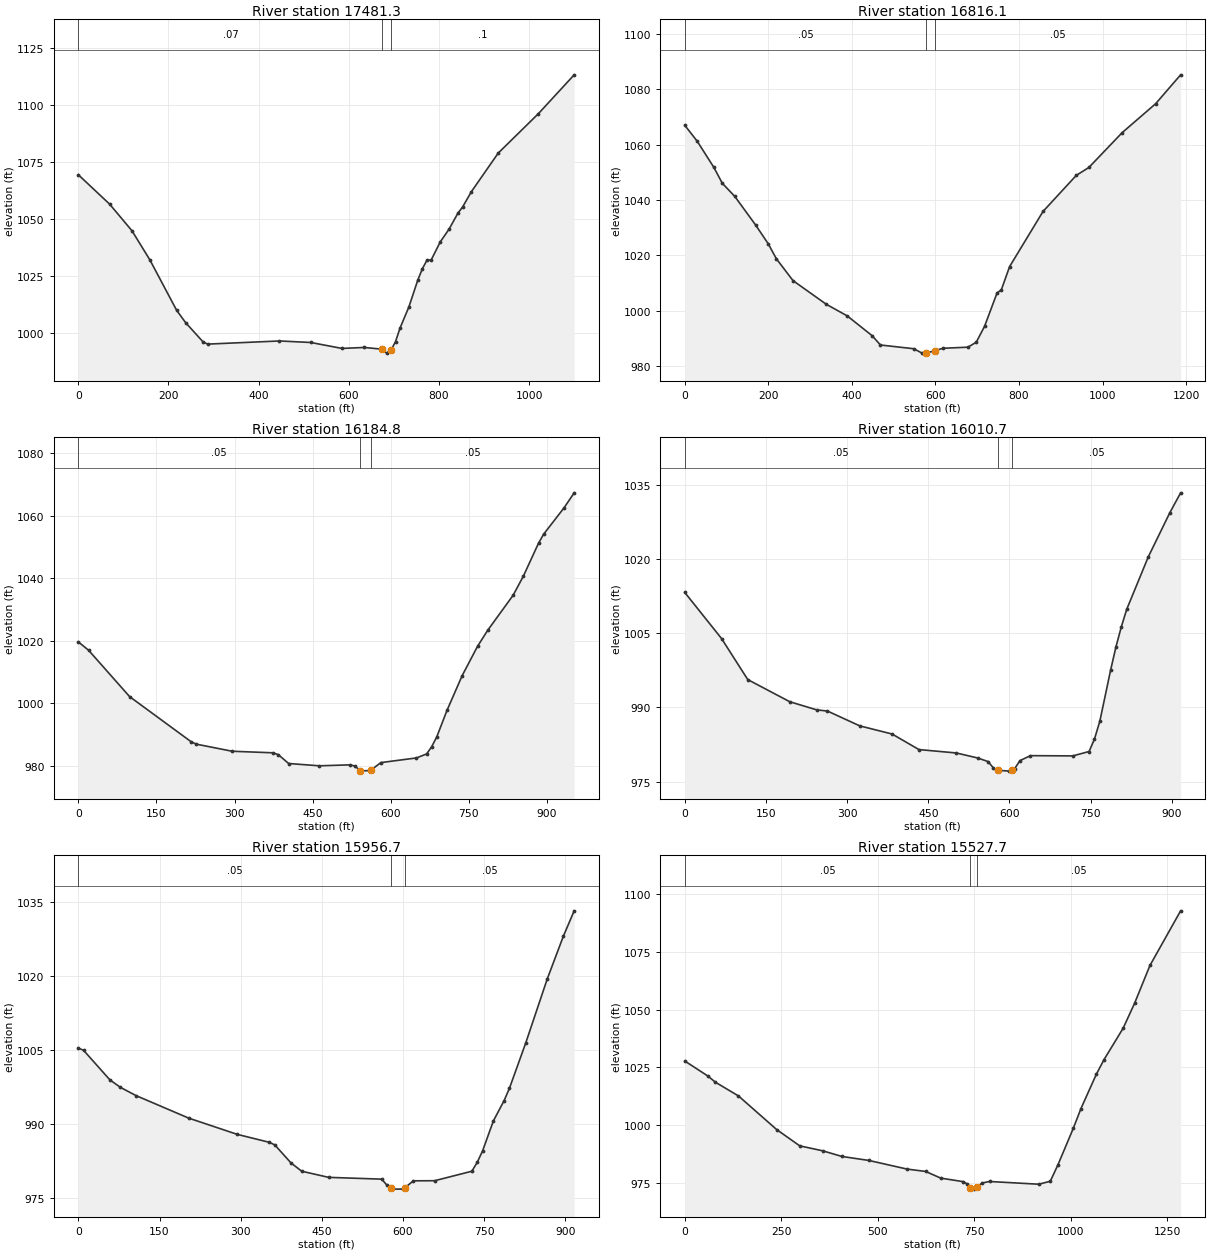
Type RM Length L Ch R = 1 ,17481.3 ,668.6,665.1,659.7
XS GIS Cut Line= 3
      1845750.44      392432.894      1846108.38      392857.322
     1846480.094      393255.674
#Sta/Elev= 30
       0 1069.39    69.4 1056.55     119 1044.89   158.6  1032.2   218.1  1010.1
     238 1004.71   277.6  996.09   287.5  995.31   446.2  996.68   515.6  996.02
   584.9  993.42   634.5  993.84   674.7  993.06     684  991.36   693.9  992.73
   703.8  996.41   713.7 1002.29   733.5 1011.62   753.3 1023.38   763.2 1028.22
   773.2  1031.9   783.1  1032.2   802.9 1039.98   822.7 1045.65   842.5 1052.71
   852.4 1055.23   872.2 1062.03   931.6 1078.87  1020.8 1096.12  1100.1 1113.11
#Mann= 3 , 0 , 0
       0     .07       0   674.7    .045       0   693.9      .1       0
Bank Sta=674.7,693.9
XS Rating Curve= 0 ,0
Exp/Cntr=0.3,0.1

Type RM Length L Ch R = 1 ,16816.1 ,624.2,631.3,639.5
XS GIS Cut Line= 3
     1845177.292      392930.989     1845648.741      393298.507
     1846120.415       393651.35
#Sta/Elev= 30
       0 1066.99    29.9 1061.19    69.7 1051.74    89.7 1046.04   119.6 1041.29
   169.4 1030.96   199.3 1024.24   219.2 1018.73     259 1010.83   338.7 1002.27
   388.6  998.09   448.3  990.93   468.3  987.55     548   986.2   567.9  984.61
   577.8  984.63   597.8  985.45   617.7  986.36   677.6  986.76   697.6  988.54
   717.6  994.34   747.5 1006.41   757.5 1007.44   777.5 1015.91   857.4 1035.83
   937.2  1048.9   967.2 1051.74    1047 1064.35  1126.9 1074.78  1186.8 1085.24
#Mann= 3 , 0 , 0
       0     .05       0   577.8    .045       0   597.8     .05       0
Bank Sta=577.8,597.8
XS Rating Curve= 0 ,0
Exp/Cntr=0.3,0.1

Type RM Length L Ch R = 1 ,16184.8 ,175.3,174.1,172.9
XS GIS Cut Line= 3
      1844975.55      393277.656     1845271.986      393742.895
     1845489.467      394079.427
#Sta/Elev= 30
       0 1019.57    19.7  1016.9    98.5 1002.06   216.7  987.62   226.6  986.85
   295.5  984.58   374.3  984.08   384.2  983.48   403.9  980.66     463  979.92
   522.1  980.23     532   979.8  541.25978.3087   541.8  978.22   561.4  978.46
     581  980.95   649.4  982.44   668.9  983.72   678.7  986.05   688.5   989.2
     708  997.63   737.3 1008.81   766.7 1018.15   786.2 1023.27   835.1  1034.5
   854.6 1040.56   883.9 1051.16   893.7 1054.04   932.8 1062.45   952.3 1067.27
#Mann= 3 , 0 , 0
       0     .05       0  541.25    .045       0   561.4     .05       0
Bank Sta=541.25,561.4
XS Rating Curve= 0 ,0
Exp/Cntr=0.3,0.1

Type RM Length L Ch R = 1 ,16010.7 ,53.9,54,54.3
XS GIS Cut Line= 5
     1844841.463      393309.027     1844920.891      393486.111
     1845057.609      393740.017     1845189.297      393922.194
     1845333.651       394073.35
#Sta/Elev= 30
       0 1013.24    67.9 1003.93   116.4  995.62   194.1  991.14   243.8   989.5
   263.7  989.26   323.4  986.26     383  984.62   432.7  981.47     502  980.78
   541.1  979.77   560.6  979.04   570.4  977.73  577.88977.2949   599.7  977.11
  605.08977.3747   609.5  977.59   619.3  979.23   638.8  980.24   717.2  980.19
   747.1  981.08     757  983.56     767  987.21   786.9  997.53   796.8 1002.25
   806.8 1006.33   816.7 1009.84   856.5 1020.44   896.4 1029.39   916.3  1033.4
#Mann= 3 , 0 , 0
       0     .05       0  577.88    .045       0  605.08     .05       0
Bank Sta=577.88,605.08
XS Rating Curve= 0 ,0
Exp/Cntr=0.3,0.1

Type RM Length L Ch R = 1 ,15956.7 ,423.4,428.9,433.8
XS GIS Cut Line= 5
     1844802.401      393346.788     1844881.828      393523.871
     1845018.547      393777.777     1845150.235      393959.954
     1845294.588      394111.111
#Sta/Elev= 30
       0 1005.39     9.7 1004.94    58.2  998.98    77.6  997.46   106.7  995.78
     204  991.23   293.5  987.95   353.2  986.33   363.1  985.81     393  982.17
   412.8  980.49   462.6  979.25   560.6  978.89   570.4  977.66  577.44977.0925
   580.2  976.87   599.7  976.88  602.84977.1011   619.3  978.55   658.4  978.57
   727.2  980.49   737.1  982.27   747.1  984.61     767  990.66   786.9  994.78
   796.8   997.3   826.7 1006.39   866.5 1019.35   896.4 1028.03   916.3 1033.15
#Mann= 3 , 0 , 0
       0     .05       0  577.44    .045       0  602.84     .05       0
Bank Sta=577.44,602.84
XS Rating Curve= 0 ,0
Exp/Cntr=0.3,0.1

Type RM Length L Ch R = 1 ,15527.7 ,973,972.5,969.3
XS GIS Cut Line= 4
      1844407.87      393328.124     1844653.095      393827.256
     1844805.005      394087.673     1845091.463      394404.513
#Sta/Elev= 30
       0  1027.8    59.6 1021.33    79.4 1018.63     139 1012.71   238.3  998.14
   297.9  991.13   357.5  988.99   407.2  986.55   476.7  984.84   575.6  981.11
   624.2  980.07   663.1   977.2   721.4  975.67   731.2  974.72  739.53972.9252
   750.6  972.44   757.8  973.21   770.1  975.08   789.5  975.74   917.2  974.56
     947  975.84   966.9  982.97  1006.6  998.71  1026.5 1007.27  1066.2 1022.03
  1086.1 1028.37  1135.7 1041.95  1165.5 1052.78  1205.3 1069.11  1284.7 1092.69
#Mann= 3 , 0 , 0
       0     .05       0  739.53    .045       0   757.8     .05       0
Bank Sta=739.53,757.8
XS Rating Curve= 0 ,0
Exp/Cntr=0.3,0.1

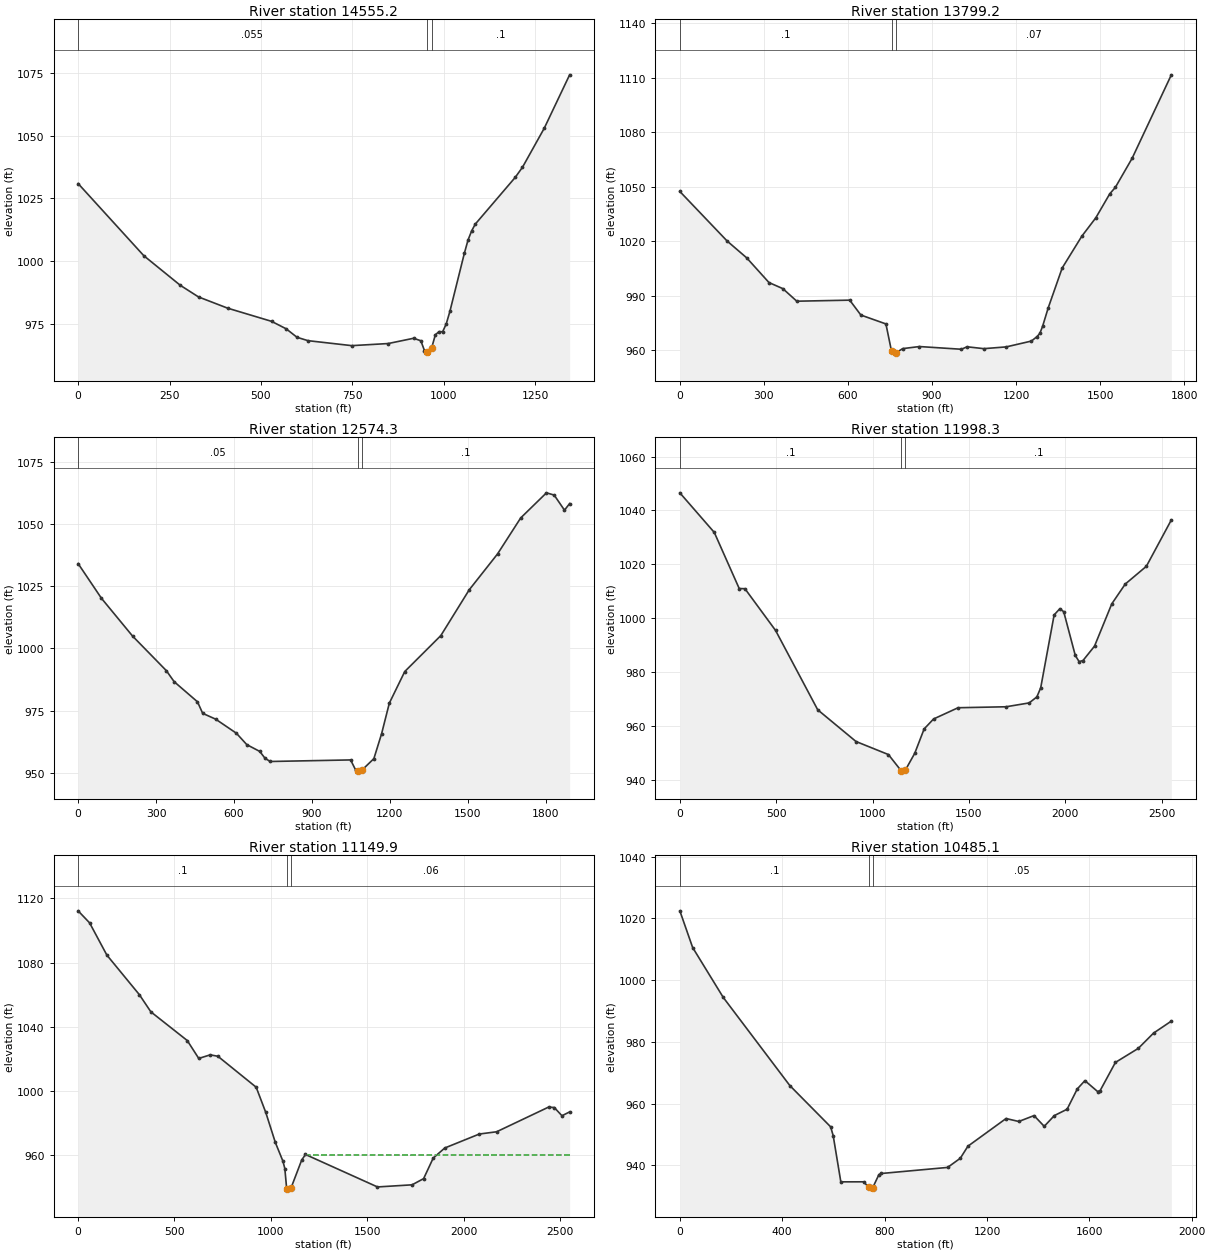
Type RM Length L Ch R = 1 ,14555.2 ,766.1,756,745.1
XS GIS Cut Line= 3
      1843693.46      393716.145     1844099.018      394404.022
     1844369.581      394878.274
#Sta/Elev= 30
       0 1030.94   179.7 1002.11   279.5  990.28   329.4  985.63   409.2  981.14
     529  975.89     569  972.91   598.9   969.5   628.8  968.16   748.6  966.17
   848.2  967.01   917.7  969.12   937.5  968.12   947.4   964.2  953.32963.5839
   957.2  963.18   967.3  965.38   977.2  970.52   987.2  971.77   997.1  971.72
    1007  974.86  1016.9  979.82  1056.6 1003.11  1066.6 1008.38  1076.5 1012.03
  1086.4 1014.73  1195.6 1033.39  1215.5 1037.45    1275 1053.03  1344.5 1074.39
#Mann= 3 , 0 , 0
       0    .055       0  953.32    .045       0   967.3      .1       0
#XS Ineff= 2 , 0
          917.26  969.09
Permanent Ineff=
       F       F
Bank Sta=953.32,967.3
XS Rating Curve= 0 ,0
Exp/Cntr=0.3,0.1

Type RM Length L Ch R = 1 ,13799.2 ,1233.8,1224.9,1215.6
XS GIS Cut Line= 3
     1842865.335      394183.159     1843490.335      394641.493
     1844316.724      395165.798
#Sta/Elev= 30
       0  1047.3   168.9    1020   238.5 1010.77     318  997.17   367.6  993.81
   417.3   986.9   606.1  987.48   645.9  979.28   735.3  974.39   755.2  959.42
   765.1  958.32  771.57958.5339     795   960.8   854.9  961.94  1004.7  960.45
  1024.7  961.81  1084.6  960.78  1164.5  961.75  1254.4  964.96  1274.4  967.41
  1284.4  969.14  1294.3  973.07  1314.3  983.21  1364.2 1005.18  1434.2 1022.67
  1484.1 1032.78    1534 1046.01    1554 1049.58  1613.9 1065.61  1753.7  1111.5
#Mann= 3 , 0 , 0
       0      .1       0   755.2    .045       0  771.57     .07       0
Bank Sta=755.2,771.57
XS Rating Curve= 0 ,0
Exp/Cntr=0.3,0.1

Type RM Length L Ch R = 1 ,12574.3 ,568.3,576,585
XS GIS Cut Line= 3
     1842594.502      395214.409     1843663.946       395419.27
     1844455.613      395554.687
#Sta/Elev= 30
       0 1034.07    89.9 1020.12   209.8 1004.93   339.6  991.07   369.6  986.64
   459.5  978.55   479.5  973.92   529.5  971.58   609.4  965.92   649.3  961.35
   699.3  958.62   719.3   955.9   739.2  954.58  1048.9  955.21  1068.9  951.03
  1077.8  950.75  1078.9  950.71  1092.8  951.15  1138.5  955.73  1168.2  965.73
    1198  978.02  1257.4  990.72  1396.3 1005.16  1505.3 1023.51  1614.4 1037.93
  1703.7 1052.41  1802.8 1062.49  1832.6 1061.58  1872.2 1055.52    1892 1058.18
#Mann= 3 , 0 , 0
       0     .05       0  1077.8    .045       0  1092.8      .1       0
Bank Sta=1077.8,1092.8
XS Rating Curve= 0 ,0
Exp/Cntr=0.3,0.1

Type RM Length L Ch R = 1 ,11998.3 ,851.6,848.4,844.2
XS GIS Cut Line= 4
     1842447.366      395447.048     1843397.887      395876.736
     1843737.033      396049.158     1844715.161      396608.072
#Sta/Elev= 30
       0 1046.55   178.8 1031.84     308 1011.02   337.8 1010.94   496.7  995.44
   715.3  965.98     914   954.2  1082.2  949.35 1149.25943.2551  1160.2   943.2
    1170  943.57  1218.7  949.81  1267.5  958.87  1316.3  962.56  1443.5  966.74
  1692.8   967.1  1812.4  968.53  1852.3  970.76  1872.2  974.12    1942 1001.22
  1971.9 1003.54  1991.8 1002.37  2051.7  986.16  2071.6  983.86  2091.6  984.27
  2151.4   989.6  2241.1 1005.33  2310.9 1012.67  2420.5 1019.27  2550.1  1036.5
#Mann= 3 , 0 , 0
       0      .1       0 1149.25    .045       0    1170      .1       0
Bank Sta=1149.25,1170
XS Rating Curve= 0 ,0
Exp/Cntr=0.3,0.1

Type RM Length L Ch R = 1 ,11149.9 ,668.8,664.8,660.4
XS GIS Cut Line= 4
     1842559.991      396459.206     1843560.999      396752.639
     1843920.815      396876.261      1844967.12      397293.831
#Sta/Elev= 30
       0 1112.26    59.6 1104.76     149 1084.72   317.9 1060.03   377.5 1049.35
   566.3 1031.49   625.9 1020.34   685.5 1022.58   725.2 1021.69   923.9 1002.41
   973.6  986.71  1023.3     968  1062.6  956.38  1072.4   951.8 1082.09939.2228
  1101.7  938.96  1104.9  939.76  1160.2  957.14  1179.7  960.53  1553.2  940.32
  1732.6  941.64  1792.5  945.49  1842.3  958.28  1902.1  964.56  2081.6  973.27
  2171.3  974.67  2440.5  990.02  2470.4  989.79  2510.3  984.65  2550.1  987.05
#Mann= 3 , 0 , 0
       0      .1       0 1082.09    .045       0  1104.9     .06       0
#XS Ineff= 2 , 0
                         1178.19          960.41
Permanent Ineff=
       F       F
Bank Sta=1082.09,1104.9
XS Rating Curve= 0 ,0
Exp/Cntr=0.3,0.1

Type RM Length L Ch R = 1 ,10485.1 ,696.8,680.3,663.3
XS GIS Cut Line= 3
     1843190.261      397206.332      1843729.05      397314.236
     1845076.272      397567.708
#Sta/Elev= 30
       0 1022.45      50 1010.57   169.8  994.38   429.6  965.86   589.2  952.48
   599.2  949.61     629  934.66   718.4  934.67   738.3  932.83   748.2   932.3
   753.3  932.72     778  937.03   787.9  937.37  1046.2  939.33  1095.8   942.3
  1125.6  946.21  1274.6  955.17  1324.3  954.21  1383.9  956.12  1423.7  952.64
  1463.4  956.13  1513.1  958.18  1552.8  964.75  1582.6  967.44  1632.3  963.91
  1642.2  964.22  1701.8  973.34  1791.2  977.89  1850.8  982.84  1920.4  986.73
#Mann= 3 , 0 , 0
       0      .1       0   738.3    .045       0   753.3     .05       0
Bank Sta=738.3,753.3
XS Rating Curve= 0 ,0
Exp/Cntr=0.3,0.1

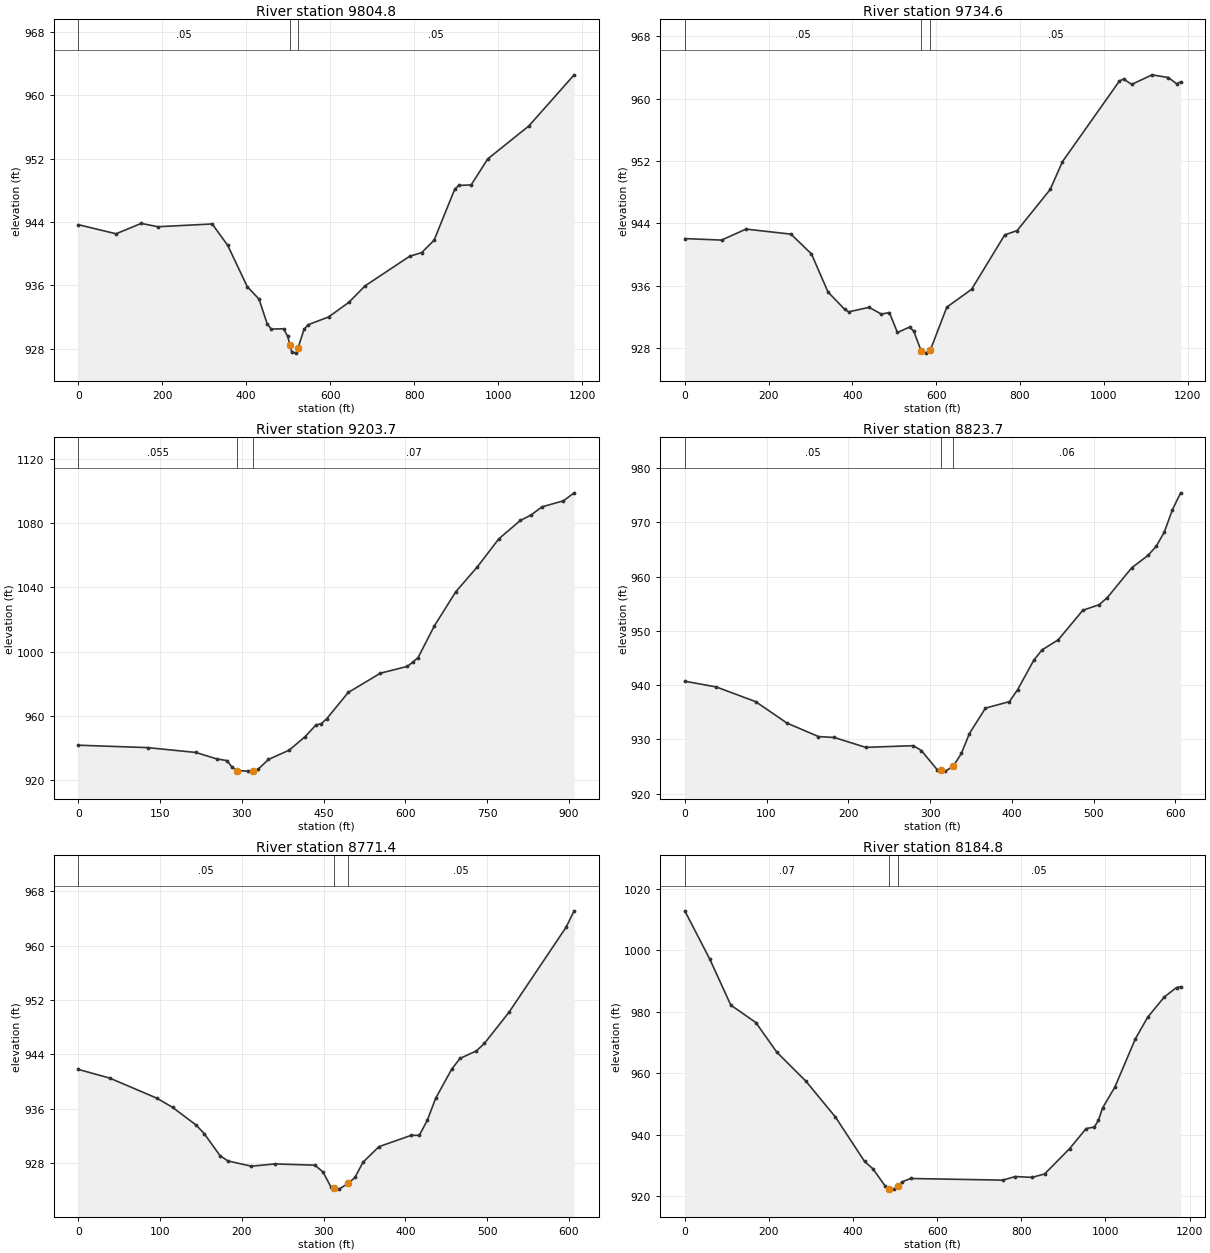
Type RM Length L Ch R = 1 ,9804.8  ,78.5,70.2,62.5
XS GIS Cut Line= 6
     1843643.113      397860.677     1843945.196      397928.385
     1844064.988       397912.76     1844176.967      397852.864
     1844343.634      397652.343     1844703.009       397600.26
#Sta/Elev= 30
       0  943.67    89.9  942.52   149.8  943.83   189.7  943.41   318.9  943.76
     356  941.05   402.5  935.84   430.4  934.28   449.9  931.16   459.7   930.5
     489  930.53   498.8  929.58   504.2  928.47   508.5  927.58   518.3  927.46
  523.11928.0853   537.8  930.47   547.6  931.05     596  932.02   644.3  933.86
   682.9  935.94   789.2  939.68   818.1  940.15   847.6  941.72   896.6  948.14
   906.4  948.62   935.9  948.69   975.2  951.96  1073.3  956.13  1181.2  962.58
#Mann= 3 , 0 , 0
       0     .05       0   504.2    .045       0  523.11     .05       0
Bank Sta=504.2,523.11
XS Rating Curve= 0 ,0
Exp/Cntr=0.3,0.1

Type RM Length L Ch R = 1 ,9734.6  ,487.5,530.9,573.6
XS GIS Cut Line= 6
     1843640.509      397915.364     1843911.342      397996.093
     1844049.363      398001.302     1844156.134      397957.031
     1844380.092      397707.031     1844689.988      397678.385
#Sta/Elev= 30
       0  942.04    87.7  941.85   146.2  943.26   253.4  942.61   302.3  940.07
   341.8  935.18   381.3  932.97   391.1  932.64     440  933.22   468.9  932.35
   488.2  932.55   507.4  929.99   536.3  930.68   546.2  930.18  563.87927.6499
   575.8  927.34   585.7  927.69   625.2  933.24   684.4  935.53   763.4  942.51
     793  943.07     872  948.35   901.1  951.91  1037.3  962.28    1047  962.52
  1066.5  961.83  1115.1  963.06    1154  962.71  1173.4  961.92  1183.2  962.15
#Mann= 3 , 0 , 0
       0     .05       0  563.87    .045       0   585.7     .05       0
Bank Sta=563.87,585.7
XS Rating Curve= 0 ,0
Exp/Cntr=0.3,0.1

Type RM Length L Ch R = 1 ,9203.7  ,348.1,380.1,412.1
XS GIS Cut Line= 4
      1843604.05      397917.968     1843752.488      398087.239
     1843846.238      398230.468     1844114.467      398667.968
#Sta/Elev= 30
       0  941.72   127.2  940.22   215.4  937.21   253.7  933.21   272.7  932.14
   282.2  927.97   291.7  925.92   310.7  925.58   320.2  925.69   329.8  926.77
   348.8  932.85   386.8  938.66   416.1  947.08   435.8  954.28   445.7   955.2
   455.5  958.13     495  974.54   554.2  986.56   603.6  990.78   613.4  993.41
   623.3  996.32   652.9 1015.89   692.4 1037.28   731.9 1052.73   771.3  1070.2
   810.8 1081.63   830.6 1085.06   850.3 1090.09   889.8 1093.86   909.5 1098.84
#Mann= 3 , 0 , 0
       0    .055       0   291.7    .045       0   320.2     .07       0
Bank Sta=291.7,320.2
XS Rating Curve= 0 ,0
Exp/Cntr=0.3,0.1

Type RM Length L Ch R = 1 ,8823.7  ,51.6,52.3,52.9
XS GIS Cut Line= 4
     1843575.404      397946.614     1843502.488      398175.781
     1843390.509      398285.156     1843411.342      398493.489
#Sta/Elev= 30
       0  940.73    38.5  939.67    86.6  936.97     125  933.01   163.5  930.53
   182.8  930.36   221.2  928.54   279.6  928.85   289.4  927.94     309  924.37
   312.9  924.29   318.8  924.16   328.5  925.08   338.3  927.44   348.1  931.09
   367.7  935.77     397  936.97     407  939.16   426.9  944.62   436.9  946.49
   456.8  948.37   486.8   953.8   506.7  954.82   516.7  956.13   546.6  961.63
   566.5  963.91   576.5  965.58   586.4  968.19   596.4  972.34   606.4  975.44
#Mann= 3 , 0 , 0
       0     .05       0   312.9    .045       0   328.5     .06       0
Bank Sta=312.9,328.5
XS Rating Curve= 0 ,0
Exp/Cntr=0.3,0.1

Type RM Length L Ch R = 1 ,8771.4  ,618.6,586.6,551
XS GIS Cut Line= 4
     1843528.529      397925.781     1843455.613      398154.947
     1843343.634      398264.322     1843364.467      398472.656
#Sta/Elev= 30
       0  941.78    38.5   940.5    96.2  937.54   115.4  936.19   144.3  933.57
   153.9  932.35   173.2  929.11   182.8  928.32   211.6  927.54   240.5  927.88
   289.4  927.69   299.2  926.69     309  924.48  312.18924.3809   318.8  924.17
   330.1  925.02   338.3  925.89   348.1  928.12   367.7  930.42     407  932.08
     417  932.09   426.9  934.32   436.9  937.51   456.8  941.85   466.8   943.4
   486.8   944.5   496.7  945.62   526.6  950.17   596.4  962.67   606.4  965.11
#Mann= 3 , 0 , 0
       0     .05       0  312.18    .045       0   330.1     .05       0
Bank Sta=312.18,330.1
XS Rating Curve= 0 ,0
Exp/Cntr=0.3,0.1

Type RM Length L Ch R = 1 ,8184.8  ,584.4,563.3,544.4
XS GIS Cut Line= 4
     1842762.904      397595.052     1843002.201      398030.506
      1843229.05      398358.072     1843402.661      398582.031
#Sta/Elev= 30
       0 1012.81    59.6  997.04   109.3  982.14   168.9  976.46   218.6  966.84
   288.2  957.33   357.8  945.76   427.3  931.26   447.2  928.86     477  923.12
  485.17 922.402   496.9  922.24   506.8  923.16   516.8  924.62   536.7   925.7
   755.9  925.17   785.8  926.34   825.6  926.06   855.5  927.19   914.9  935.44
     954  941.94   973.5  942.46   983.3   944.6     993   948.6  1022.4  955.46
  1071.2  971.18  1100.5   978.2  1139.6  984.74  1168.9  987.85  1178.7  988.09
#Mann= 3 , 0 , 0
       0     .07       0  485.17    .045       0   506.8     .05       0
Bank Sta=485.17,506.8
XS Rating Curve= 0 ,0
Exp/Cntr=0.3,0.1