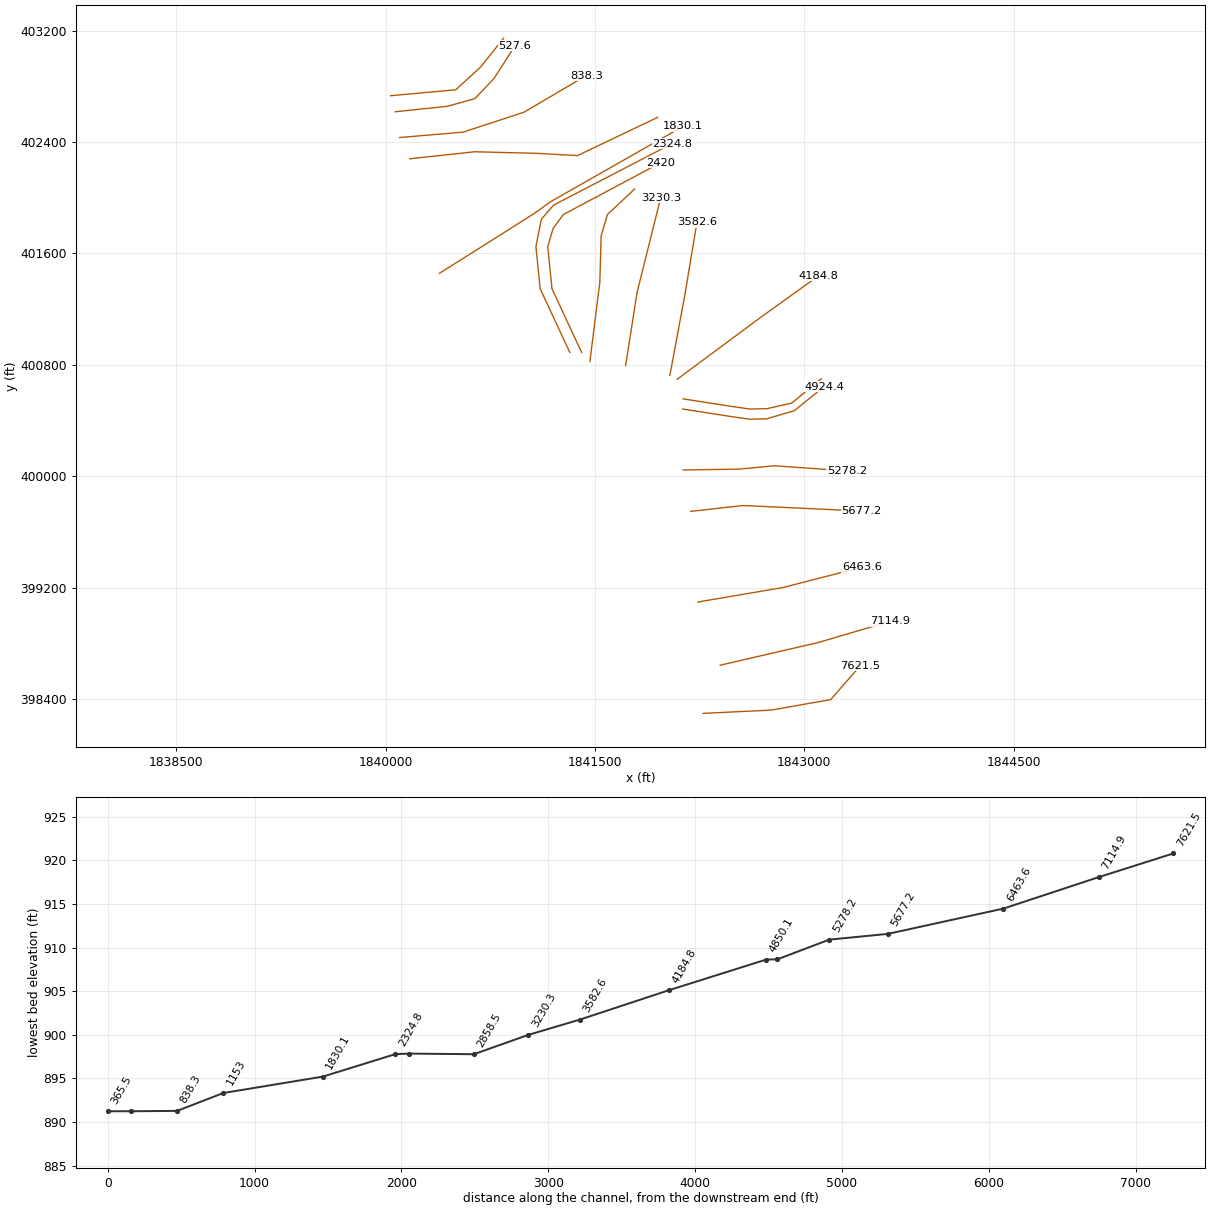
HEC-RAS study CobunCk.prj: CobunCk

--- CobunCk.g01 (geometry) --- (continued)

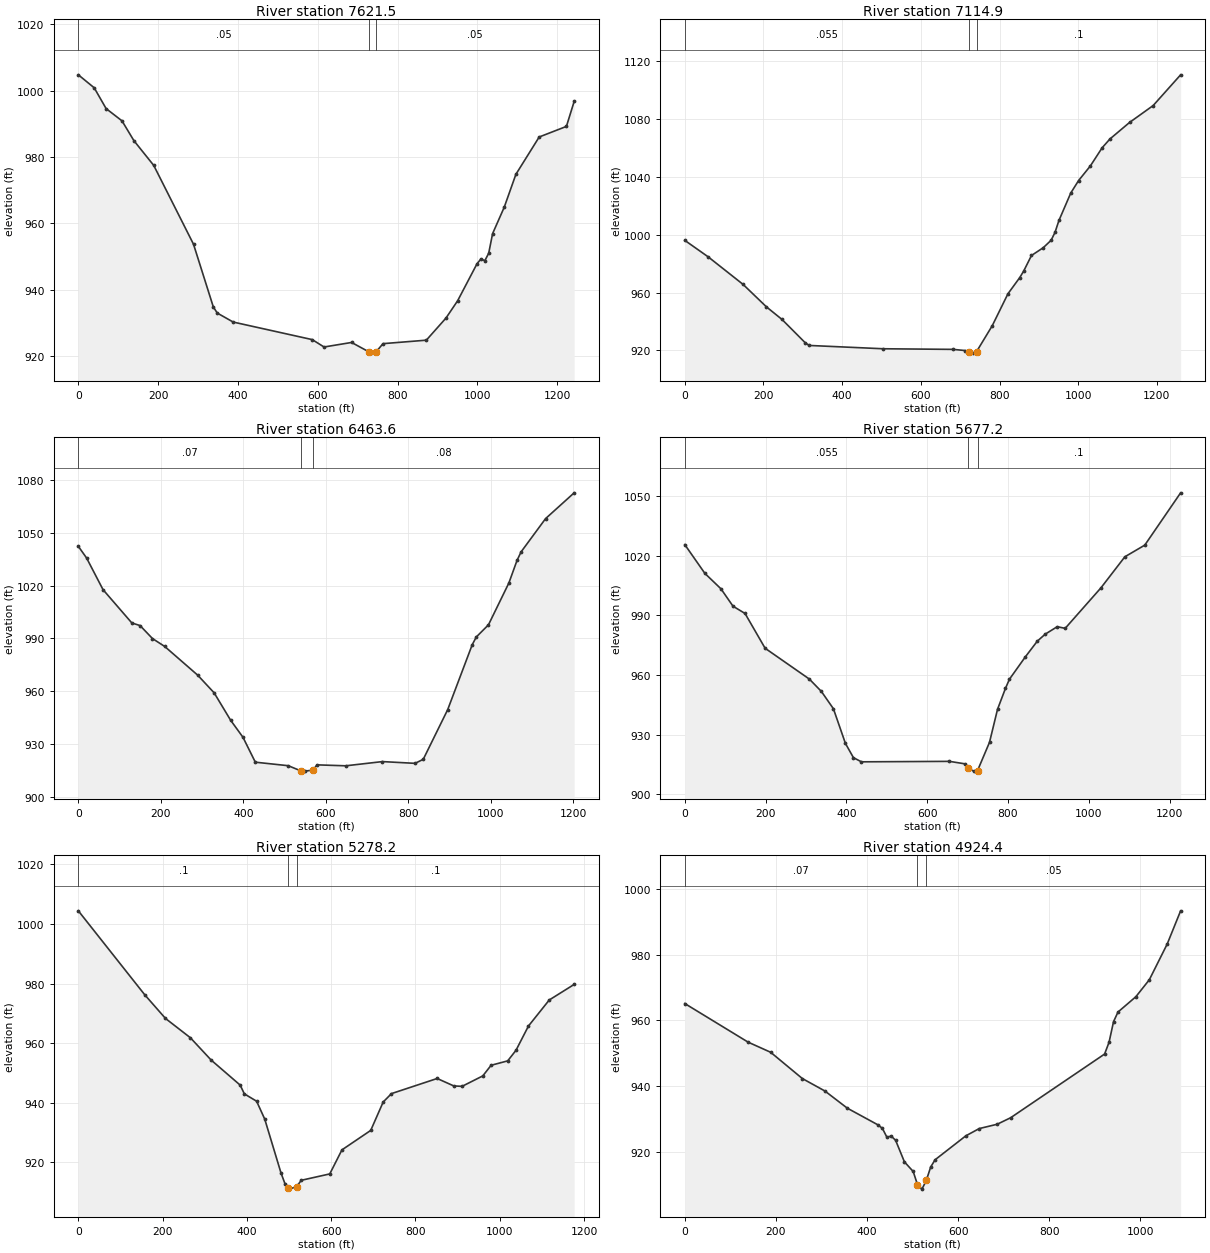
Type RM Length L Ch R = 1 ,7621.5  ,504.1,506.6,509.2
XS GIS Cut Line= 4
     1842275.057      398298.177     1842762.036      398321.614
      1843189.12      398397.135     1843400.057      398639.322
#Sta/Elev= 30
       0  1004.8    39.8 1000.88    69.6  994.61   109.4  990.91   139.3  984.92
     189  977.45   288.6  953.67   338.3  934.72   348.2  932.89     388  930.18
   586.1  924.88   615.7  922.65   684.7  924.02   729.1  921.12     734   920.8
  744.76921.0061   763.5  923.66     872  924.71   921.2  931.38   950.4   936.6
   999.1   947.8  1008.8  949.21  1018.6  948.71  1028.3  950.96    1038  956.86
  1067.2  964.84  1096.4  974.77  1154.8  986.04    1223  989.23  1242.4  996.76
#Mann= 3 , 0 , 0
       0     .05       0   729.1    .045       0  744.76     .05       0
Bank Sta=729.1,744.76
XS Rating Curve= 0 ,0
Exp/Cntr=0.3,0.1

Type RM Length L Ch R = 1 ,7114.9  ,658.8,651.3,648
XS GIS Cut Line= 3
     1842397.347      398644.087     1843100.347       398806.88
     1843616.995      398959.434
#Sta/Elev= 30
       0  996.08    59.3   984.7   148.3  965.59   207.6  950.06   247.1  941.38
   306.4  925.18   316.3   923.4   504.1  921.11   682.1  920.68   711.7   919.9
   721.6  918.63   731.6  918.09   741.6  919.14   781.5  937.05   821.4  959.15
   851.3   970.3   861.3  974.79   881.2  985.62   911.1     991   931.1  996.14
   941.1 1001.66     951 1009.84     981 1028.79  1000.9 1037.43  1030.9 1047.56
  1060.8 1060.12  1080.7 1066.22  1130.6 1077.65  1190.5 1089.32  1260.3 1110.57
#Mann= 3 , 0 , 0
       0    .055       0   721.6    .045       0   741.6      .1       0
Bank Sta=721.6,741.6
XS Rating Curve= 0 ,0
Exp/Cntr=0.3,0.1

Type RM Length L Ch R = 1 ,6463.6  ,784.8,786.4,782.6
XS GIS Cut Line= 3
     1842237.848      399097.772     1842847.974      399201.822
     1843413.078      399347.656
#Sta/Elev= 30
       0 1042.48      20 1035.85    59.9 1017.81   129.8  998.84   149.7  997.37
   179.7  989.99   209.6  985.45   289.5  969.12   329.4  959.05   369.4  943.45
   399.3  933.76   429.3  919.56   509.1  917.56   539.1  914.68     549  914.47
     569  915.04     579  918.04   648.6   917.5   737.6   919.9   816.8   918.9
   836.6   921.2   895.9   949.5   955.3  986.42   965.2  990.84   994.8   997.8
  1044.3 1021.63  1064.1 1034.51    1074 1039.36  1133.3 1058.27  1202.6 1072.95
#Mann= 3 , 0 , 0
       0     .07       0   539.1    .045       0     569     .08       0
Bank Sta=539.1,569
XS Rating Curve= 0 ,0
Exp/Cntr=0.3,0.1

Type RM Length L Ch R = 1 ,5677.2  ,395.5,399,401.5
XS GIS Cut Line= 4
     1842186.136      399748.248     1842561.516      399790.364
     1842957.349      399772.135     1843410.029      399750.589
#Sta/Elev= 30
       0 1025.71    49.7 1011.22    89.5 1003.44   119.3  994.69   149.1  991.01
   198.8  973.49   308.2  957.97     338  951.74   367.8  943.02   397.6  925.52
   417.4  918.35   437.2  916.26   655.1  916.49   694.7   915.2     702  913.13
   714.6  911.57   724.5  911.81   754.2   926.1     774  942.71   793.7  953.29
   803.5  957.88     843  969.18   872.5  977.07   892.2  980.61   921.8  984.35
   941.5  983.52  1030.1 1003.96  1089.2 1019.58  1138.5 1025.46  1227.2 1051.81
#Mann= 3 , 0 , 0
       0    .055       0     702    .045       0   724.5      .1       0
Bank Sta=702,724.5
XS Rating Curve= 0 ,0
Exp/Cntr=0.3,0.1

Type RM Length L Ch R = 1 ,5278.2  ,355.5,353.9,352.2
XS GIS Cut Line= 4
     1842131.828      400045.572     1842535.598      400051.815
     1842785.164      400075.687     1843305.998      400038.794
#Sta/Elev= 30
       0 1004.43   157.6  976.22   206.8  968.27   265.9  961.78   315.2  954.28
   384.1  945.86     394  942.92   423.1  940.45   442.4  934.43     481  916.33
   490.6  912.65  498.32911.2507   500.2  910.91   517.8  911.75   529.2  913.88
   596.7  916.02   625.6   924.1   693.9  930.64   723.5  940.19   743.2  943.01
   851.6  948.09     891  945.59   910.7  945.45   959.9  948.96   979.6  952.53
    1019  954.01  1038.7  957.57  1068.3  965.73  1117.6  974.47  1176.7   979.7
#Mann= 3 , 0 , 0
       0      .1       0  498.32    .045       0   517.8      .1       0
Bank Sta=498.32,517.8
XS Rating Curve= 0 ,0
Exp/Cntr=0.3,0.1

Type RM Length L Ch R = 1 ,4924.4  ,74.3,74.3,74.2
XS GIS Cut Line= 6
     1842129.224      400483.072     1842462.557      400430.989
     1842605.786      400410.156     1842730.786       400412.76
     1842928.703      400471.354     1843142.245      400644.531
#Sta/Elev= 30
       0  965.15   138.9   953.4   188.5  950.31     258  942.32   307.6  938.52
   356.7   933.3   424.2   928.2   433.9  927.12   443.5   924.5   453.2  924.78
   462.8  923.52   482.1  916.96   501.4  914.02   510.8  910.03   520.6  908.65
   530.2   911.3   539.8  915.38   549.4  917.58     617  924.88   646.5  927.09
   685.8   928.4   715.3  930.38   921.6  949.77   931.4  953.37   941.2  959.62
     951  962.56   990.3  967.23  1019.8  972.39    1059  983.25  1088.5  993.37
#Mann= 3 , 0 , 0
       0     .07       0   510.8    .045       0   530.2     .05       0
Bank Sta=510.8,530.2
XS Rating Curve= 0 ,0
Exp/Cntr=0.3,0.1

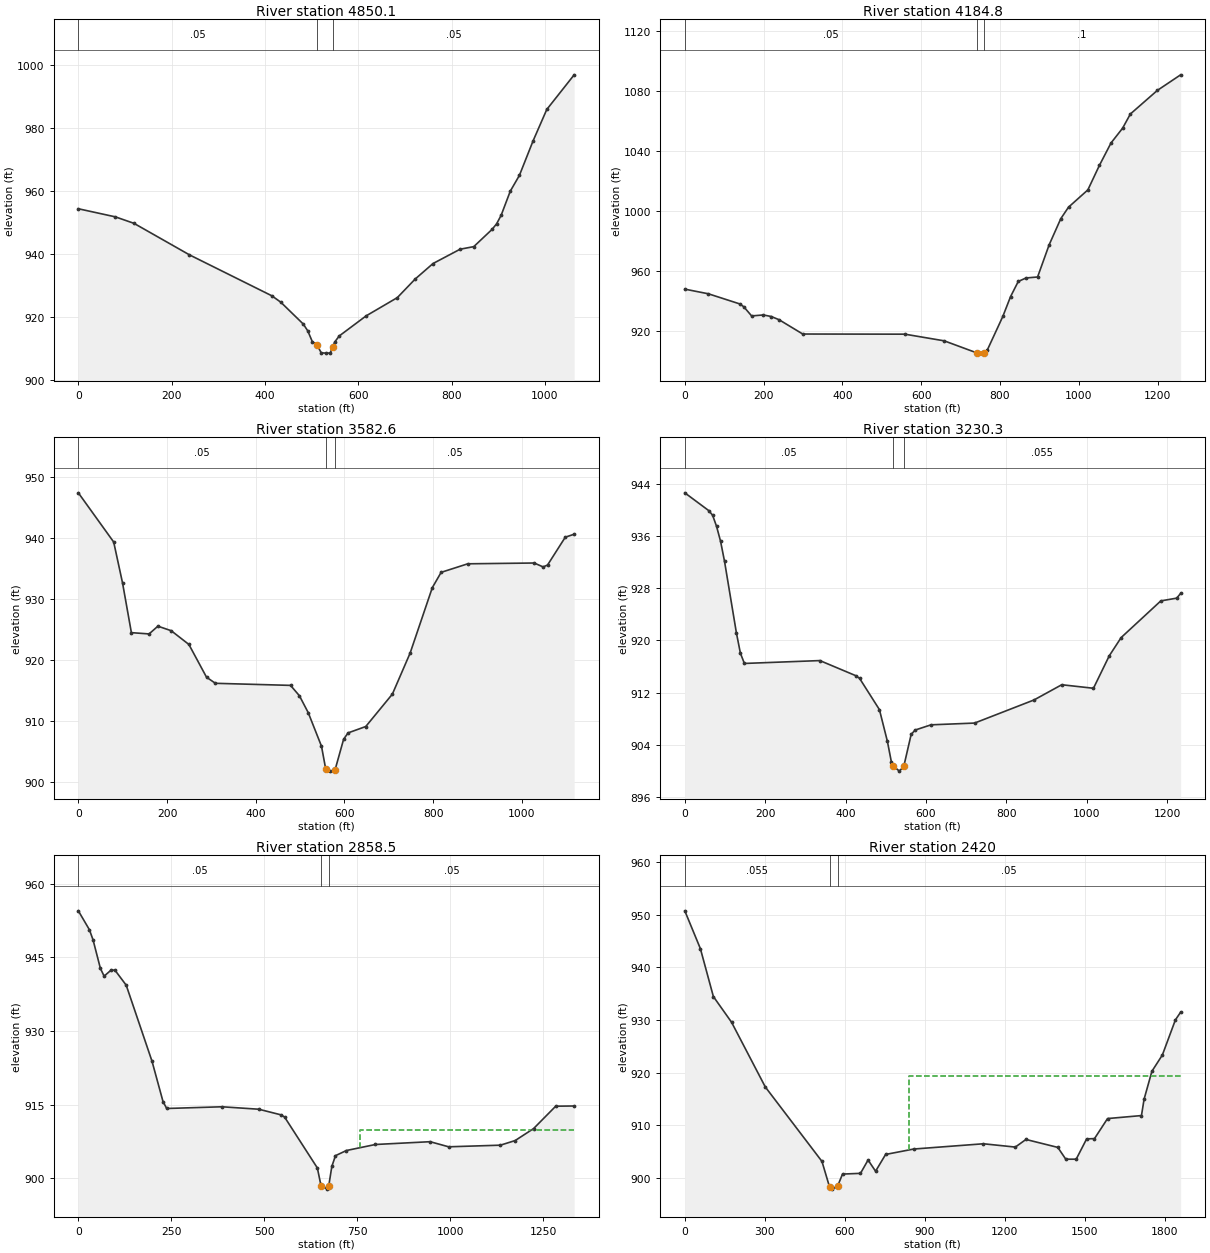
Type RM Length L Ch R = 1 ,4850.1  ,651,665.3,679.2
XS GIS Cut Line= 6
     1842131.828      400555.989     1842465.161      400503.906
     1842608.391      400483.072     1842733.391      400485.677
     1842910.474      400526.041     1843121.411       400700.52
#Sta/Elev= 30
       0  954.37    79.4   951.8   119.1  949.76   238.2  939.76   414.6   926.8
   433.9  924.76   482.1  917.83   491.7  915.67   501.4  912.26     511  911.29
   520.6  908.73   530.2  908.63   539.8  908.66  545.02910.5522   549.4  912.14
     559  914.06   616.7  920.43   683.6  926.22   721.8   932.1   760.1  937.02
   818.1  941.55   847.4  942.37   886.5  947.82   896.3  949.59   906.1  952.32
   925.6  959.94   945.2  964.95   974.5  975.88  1003.8  985.82  1062.5   996.8
#Mann= 3 , 0 , 0
       0     .05       0     511    .045       0  545.02     .05       0
Bank Sta=511,545.02
XS Rating Curve= 0 ,0
Exp/Cntr=0.3,0.1

Type RM Length L Ch R = 1 ,4184.8  ,585.1,602.2,619.6
XS GIS Cut Line= 3
     1842088.287      400696.199     1842689.174      401142.332
     1843103.286      401440.492
#Sta/Elev= 30
       0  947.81    59.9   944.7   139.7  937.93   149.7  936.05   169.6  929.94
   199.6  930.57   219.5  929.54   239.5  927.37   299.4  917.85   558.8  917.75
   658.6   913.3   740.9   905.3   748.4   905.1  758.78905.2249     768  907.21
   807.3  929.56   826.9  942.76   846.5  952.93   866.2  955.26   895.6  955.92
     925  977.44   954.5  994.84   974.1 1002.52  1023.2 1014.05  1052.6 1030.45
    1082 1045.37  1111.5 1055.27  1131.1  1064.7  1199.8 1080.49  1258.7 1090.85
#Mann= 3 , 0 , 0
       0     .05       0   740.9    .045       0  758.78      .1       0
Bank Sta=740.9,758.78
XS Rating Curve= 0 ,0
Exp/Cntr=0.3,0.1

Type RM Length L Ch R = 1 ,3582.6  ,352,352.3,350.1
XS GIS Cut Line= 3
     1842036.921      400725.405     1842144.559       401303.53
     1842231.365      401826.099
#Sta/Elev= 30
       0  947.35    79.7  939.29    99.7  932.57   119.6  924.44   159.5  924.23
   179.4   925.5   209.3  924.76   249.2  922.51     289  917.14     309  916.14
   478.4   915.8   498.4   914.1   518.3  911.33   548.2  905.83  557.86902.0336
   568.1  901.75   578.8901.9635     598  906.96     608  908.01     648  909.06
     708  914.37     748  921.09     798  931.81   817.9  934.32   877.9  935.72
  1027.8  935.85  1047.8  935.21  1057.8  935.52  1097.8  940.08  1117.8  940.57
#Mann= 3 , 0 , 0
       0     .05       0  557.86    .045       0   578.8     .05       0
Bank Sta=557.86,578.8
XS Rating Curve= 0 ,0
Exp/Cntr=0.3,0.1

Type RM Length L Ch R = 1 ,3230.3  ,367.5,371.7,377.3
XS GIS Cut Line= 3
     1841719.646      400793.547     1841802.112      401320.891
     1841971.382      402000.144
#Sta/Elev= 30
       0  942.61    59.3   939.9    69.2  939.18    79.1  937.46      89  935.19
    98.8  932.14   128.5  921.13   138.4  918.04   148.3  916.48   336.1  916.92
     425  914.62   434.9   914.2   484.3  909.41   504.1  904.56     514  901.41
  518.92900.7839   533.8  899.99  544.87900.7102   563.3  905.62   573.2  906.28
   612.6  907.08   721.1  907.35     869  910.89     938  913.22  1016.9  912.68
  1056.3  917.66  1085.9  920.45  1184.5  926.06  1223.9  926.48  1233.8   927.2
#Mann= 3 , 0 , 0
       0     .05       0  518.92    .045       0  544.87    .055       0
Bank Sta=518.92,544.87
XS Rating Curve= 0 ,0
Exp/Cntr=0.3,0.1

Type RM Length L Ch R = 1 ,2858.5  ,430.4,438.5,445.2
XS GIS Cut Line= 5
     1841463.993      400824.447     1841535.184      401394.675
     1841544.568      401726.439     1841589.707      401879.217
      1841784.75      402063.078
#Sta/Elev= 30
       0  954.51    29.7  950.67    39.6  948.59    59.4  942.76    69.4  941.19
    89.2   942.5    99.1  942.35   128.8  939.35   198.2  923.85   227.9   915.6
   237.8  914.21   386.4  914.56   485.5  914.06   544.9  912.92   554.8  912.47
     643  902.09   652.8   898.5   670.2  897.77  673.48898.3333     682   902.4
   691.8  904.59   721.1  905.64   799.2  906.87   946.4  907.44   996.2   906.4
  1135.4  906.73  1175.1  907.67  1224.7  910.11  1284.3  914.68  1333.9  914.72
#Mann= 3 , 0 , 0
       0     .05       0   652.8    .045       0  673.48     .05       0
#XS Ineff= 2 , 0
                          759.01          909.87
Permanent Ineff=
       F       F
Bank Sta=652.8,673.48
XS Rating Curve= 0 ,0
Exp/Cntr=0.3,0.1

Type RM Length L Ch R = 1 ,2420    ,95.7,95.3,96.4
XS GIS Cut Line= 6
     1841404.976      400889.033     1841192.303      401346.932
     1841161.921      401648.582     1841200.656      401780.006
     1841274.267      401879.737     1841970.784      402251.243
#Sta/Elev= 30
       0  950.73    58.5  943.54   107.2  934.44   175.4  929.56     302  917.26
   514.6  903.11   543.5  898.18   553.1  897.84  573.32898.4039   591.7   900.7
   659.2  900.84   687.6  903.37   715.8  901.24   753.4  904.43   858.8  905.46
  1120.6  906.46  1240.1  905.83    1280  907.28  1399.5  905.77  1429.4  903.53
  1468.5  903.53  1507.7  907.39  1537.1  907.44  1586.1  911.25  1713.4  911.82
  1723.2  914.93  1752.6  920.24  1791.8  923.33  1840.7     930  1860.3  931.47
#Mann= 3 , 0 , 0
       0    .055       0   543.5    .045       0  573.32     .05       0
#XS Ineff= 2 , 0
                           840.8          919.28
Permanent Ineff=
       F       F
Bank Sta=543.5,573.32
XS Rating Curve= 0 ,0
Exp/Cntr=0.3,0.1

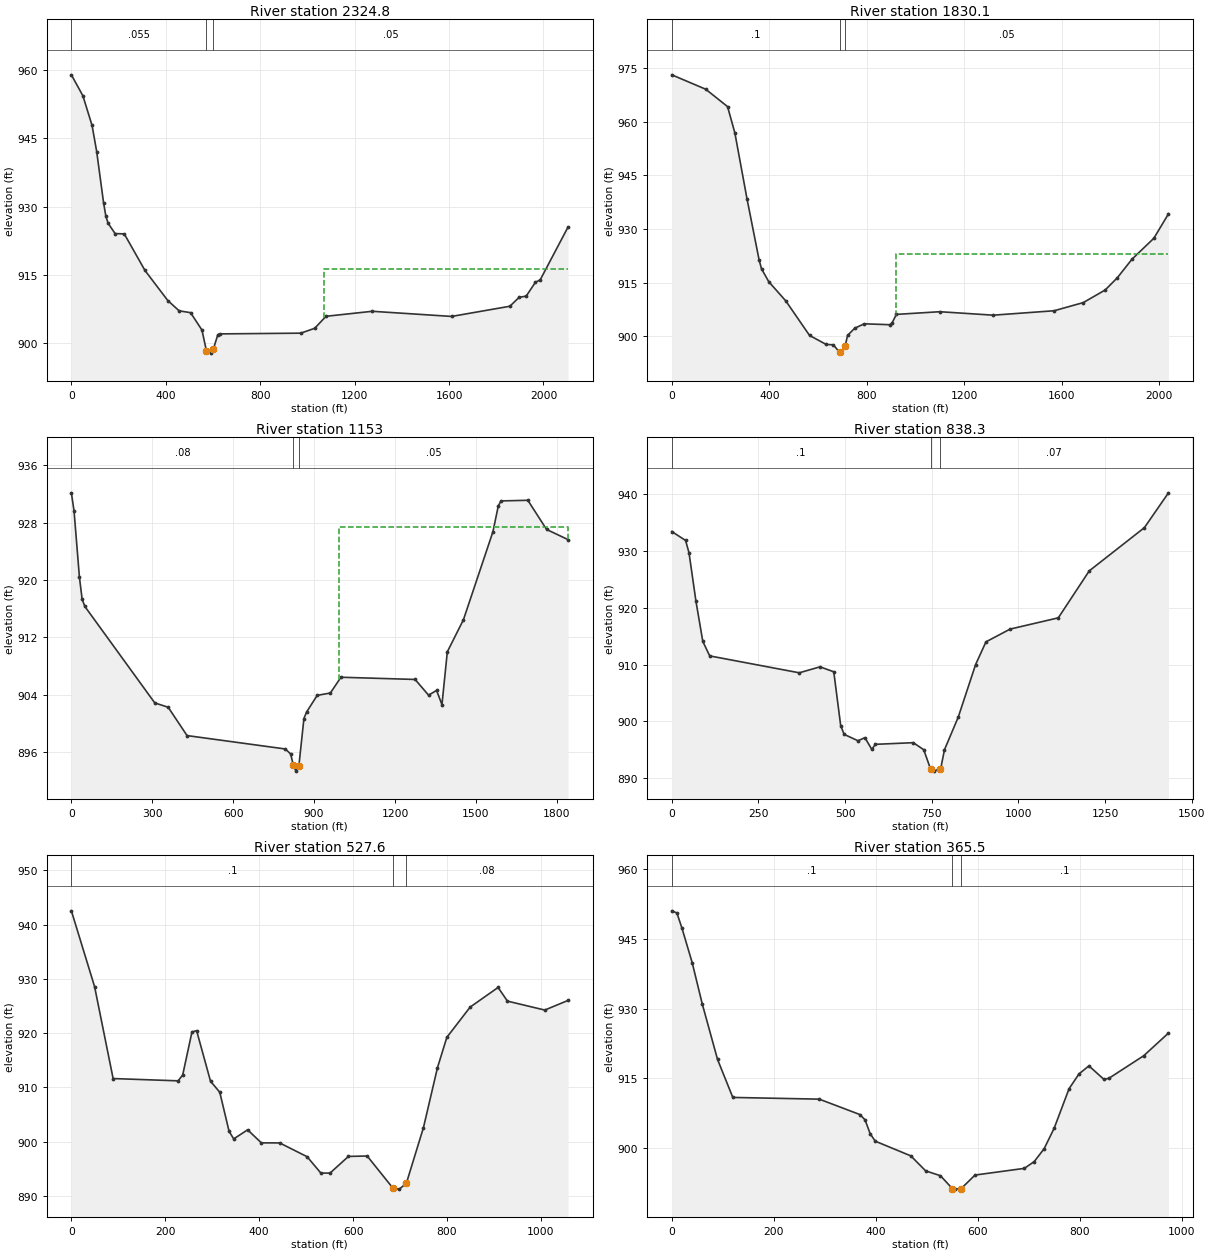
Type RM Length L Ch R = 1 ,2324.8  ,518.7,494.7,465.4
XS GIS Cut Line= 6
     1841320.341      400889.033     1841107.667      401346.932
     1841077.285      401648.582     1841116.264      401845.677
     1841204.321      401947.282     1842054.118      402389.264
#Sta/Elev= 30
       0  958.98    48.7  954.38    87.7  947.84   107.2  942.11   136.4  930.84
   146.2  927.86   155.9  926.32   185.1  924.07   224.1     924   311.8  915.96
   408.4  909.35   456.6  907.08   504.9  906.68   553.1  902.86   572.4  898.24
   591.7  897.78   601.3  898.65   620.6  901.85   630.2  902.01   971.9  902.17
  1030.8  903.24  1078.8  905.88  1274.7  906.98    1611  905.85  1857.7  908.09
  1897.1  910.06  1926.7  910.31  1966.2  913.38  1985.9  913.87  2104.2  925.52
#Mann= 3 , 0 , 0
       0    .055       0   572.4    .045       0   601.3     .05       0
#XS Ineff= 2 , 0
                         1072.24          916.23
Permanent Ineff=
       F       F
Bank Sta=572.4,601.3
XS Rating Curve= 0 ,0
Exp/Cntr=0.3,0.1

Type RM Length L Ch R = 1 ,1830.1  ,684.1,677.1,662.4
XS GIS Cut Line= 5
     1840386.582      401457.776     1840782.146      401707.175
     1841062.094      401885.127     1841184.403       401972.49
     1842129.639      402511.659
#Sta/Elev= 30
       0  973.22   139.3  969.18   228.8  964.31   258.7  956.96   308.4  938.53
   358.2  921.34   368.1  918.83     398  915.21   467.6  909.85   565.2  900.16
   633.5  897.63   662.8  897.54  688.66895.4066     692   895.2   711.5   897.3
   721.3  900.18   750.6  902.19   789.6  903.42   893.3  903.17   902.7  903.53
   921.5  906.06  1099.4  906.81    1319  905.84  1568.6  907.08  1688.4  909.37
  1778.3  912.91  1828.2  916.35  1888.1  921.53  1977.9  927.41  2037.8  934.26
#Mann= 3 , 0 , 0
       0      .1       0  688.66    .045       0   711.5     .05       0
#XS Ineff= 2 , 0
                          918.06          922.92
Permanent Ineff=
       F       F
Bank Sta=688.66,711.5
XS Rating Curve= 0 ,0
Exp/Cntr=0.3,0.1

Type RM Length L Ch R = 1 ,1153    ,319,314.7,321.3
XS GIS Cut Line= 5
     1840172.882      402279.515     1840638.917      402330.005
     1841081.517      402318.698     1841374.521      402302.343
     1841949.083      402576.764
#Sta/Elev= 30
       0  932.15      10  929.58    29.9  920.35    39.9   917.3    49.9   916.3
   309.2  902.84     359  902.23   428.9  898.28   793.4  896.41   813.1  895.71
     823  894.16   832.8  893.32   843.6  894.07   862.3  900.66   872.2  901.57
   911.5  903.89   960.4  904.22   999.5  906.42  1274.6  906.11  1324.4  903.92
  1354.2  904.58  1374.1   902.6    1394  909.97  1453.7  914.44  1563.1  926.72
    1583  930.32    1593  931.02  1692.5  931.11  1762.1  927.04  1841.7  925.62
#Mann= 3 , 0 , 0
       0     .08       0     823    .045       0   843.6     .05       0
#XS Ineff= 2 , 0
                          992.64          927.36
Permanent Ineff=
       F       F
Bank Sta=823,843.6
XS Rating Curve= 0 ,0
Exp/Cntr=0.3,0.1

Type RM Length L Ch R = 1 ,838.3   ,299.5,310.7,322
XS GIS Cut Line= 4
     1840100.831      402432.002      1840556.56      402471.064
     1840992.758      402614.293     1841437.637       402876.88
#Sta/Elev= 30
       0  933.38    39.8  931.81    49.7  929.64    69.6  921.17    89.5  914.06
   109.4  911.52   367.9  908.55   427.6   909.6   467.4  908.73   487.3  899.28
   497.3  897.73   537.2  896.61   557.2  897.15   577.2  895.08   587.2  895.98
   696.9  896.27   726.9  895.03   746.8  891.61   756.8  891.27  772.56891.6942
   776.8  891.99   786.8  895.03   826.7  900.79   876.6     910   906.5  913.99
   976.1  916.23  1115.2  918.21  1204.6  926.47  1363.6  934.06  1433.1  940.18
#Mann= 3 , 0 , 0
       0      .1       0   746.8    .045       0  772.56     .07       0
Bank Sta=746.8,772.56
XS Rating Curve= 0 ,0
Exp/Cntr=0.3,0.1

Type RM Length L Ch R = 1 ,527.6   ,166.1,162.1,158.9
XS GIS Cut Line= 5
     1840070.883      402617.332     1840444.147      402656.394
     1840641.196       402711.95     1840777.915      402857.349
     1840927.654      403091.724
#Sta/Elev= 30
       0  942.55    49.4  928.58    88.9  911.62   227.2   911.2     237  912.26
   256.8  920.21   266.7  920.45   296.3  911.13     316   909.1   335.8   901.9
   345.7  900.49   375.3  902.17   404.6  899.76   443.6  899.75     502  897.21
   531.3  894.19   550.8  894.19     590  897.26   629.9  897.34  685.26891.3635
   698.4  891.23   713.4  892.32   749.7  902.56   779.6  913.62   799.5  919.21
   849.2   924.8   908.7  928.42   928.6   925.9  1008.1  924.25  1057.7  926.03
#Mann= 3 , 0 , 0
       0      .1       0  685.26    .045       0   713.4     .08       0
Bank Sta=685.26,713.4
XS Rating Curve= 0 ,0
Exp/Cntr=0.3,0.1

Type RM Length L Ch R = 1 ,365.5   ,364.6,365.5,365.4
XS GIS Cut Line= 4
     1840036.535      402732.482     1840503.135      402774.797
      1840681.24      402938.546     1840845.189      403144.241
#Sta/Elev= 30
       0  950.99      10  950.53    19.9  947.28    39.9  939.89    59.8  930.96
    89.7  919.07   119.6  910.92   289.1  910.55   368.8  907.24   378.8   906.1
   388.8  903.14   398.7  901.53   468.5  898.37   497.6  895.15   526.6  894.11
     550  891.33   555.6  891.23  567.25891.3506   594.3  894.25   691.1  895.69
   710.5  897.16   729.9  899.93   749.4   904.3   778.6  912.78   798.1  915.97
   817.6   917.7   846.8  914.81   856.6  915.02   924.8  919.86   973.5  924.74
#Mann= 3 , 0 , 0
       0      .1       0     550    .045       0  567.25      .1       0
Bank Sta=550,567.25
XS Rating Curve= 0 ,0
Exp/Cntr=0.3,0.1

Chan Stop Cuts=-1
Use User Specified Reach Order=0
Composite Channel Slope=5